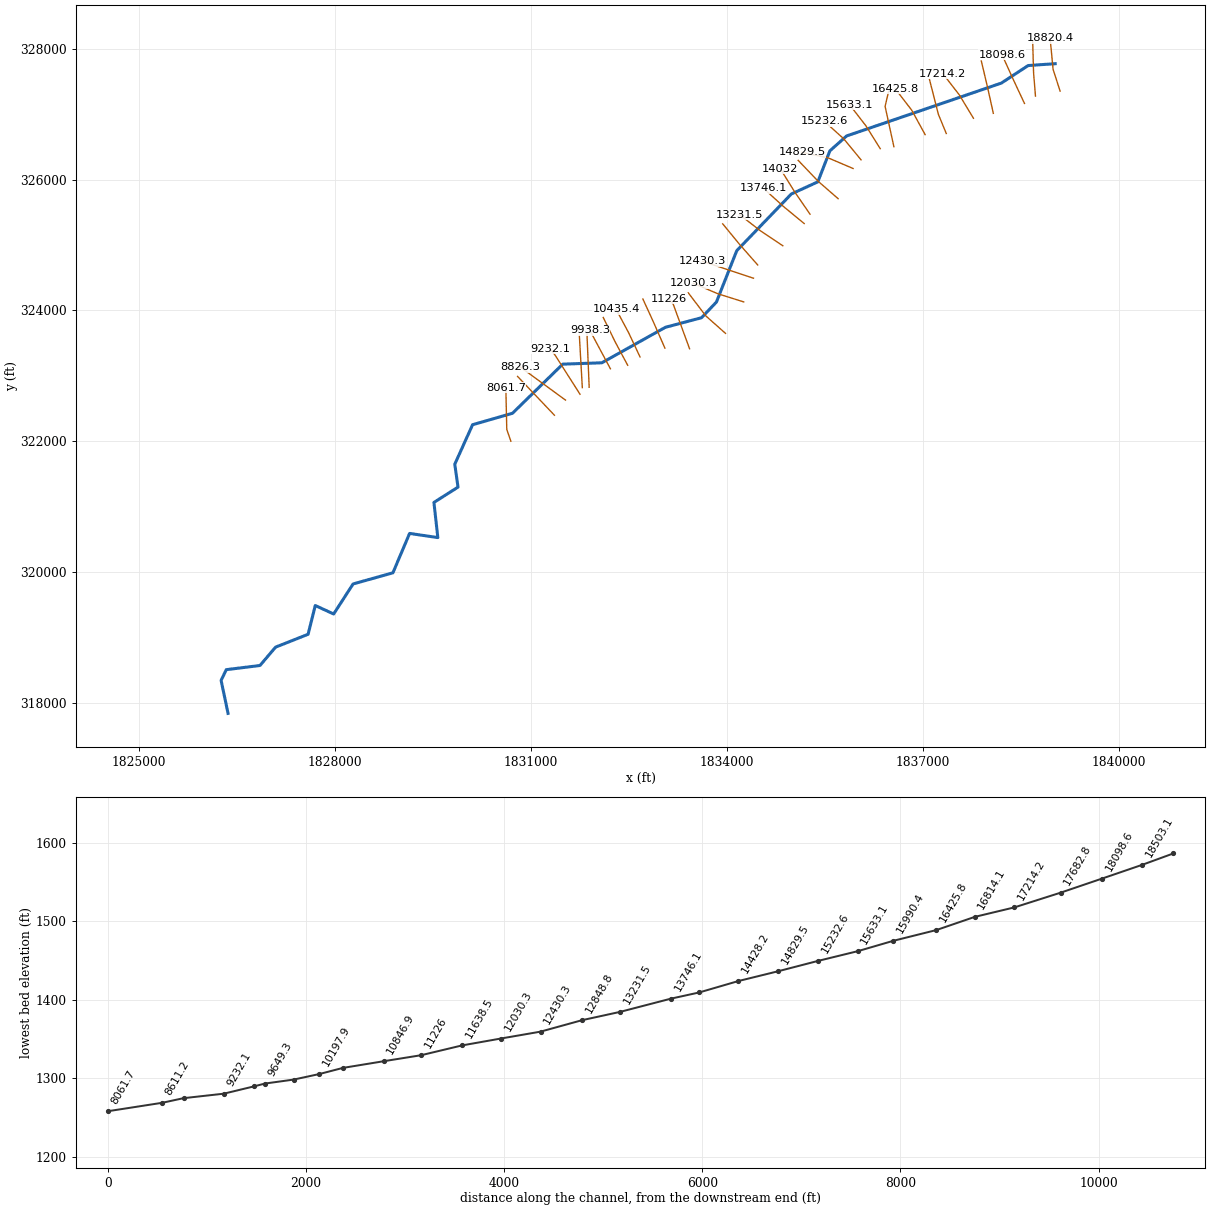
--- HrsCrk.prj (project) ---

Proj Title=HrsCrk
Current Plan=p01
Default Exp/Contr=0,0
English Units
Geom File=g01
Flow File=f01
Plan File=p01
BEGIN DESCRIPTION:
END DESCRIPTION:
DSS Export Rating Curves= 0
DSS Export Rating Curve Sorted= 0
DSS Export Volume Flow Curves= 0
DXF OffsetX= 0
DXF OffsetY= 0
DXF ScaleX= 0
DXF ScaleY= 0

--- HrsCrk.p01 (plan) ---

Plan Title=Floodplain
Program Version=4.00
Geom File=g01
Flow File=f01
K Sum by GR=0
Std Step Tol=0.01
Critical Tol=0.01
Num of Std Step Trials=20
Max Error Tol=0.3
Flow Tol Ratio=0.001
Split Flow NTrial=30
Split Flow Tol=0.02
Split Flow Ratio=0.02
Log Output Level=0
Friction Slope Method=1
Unsteady Friction Slope Method=2
Unsteady Bridges Friction Slope Method=1
Global Log Level=0
CheckData=False
Run HTab=0
Run UNet=0
Run PostProcess=0
UNET Theta=0
UNET Theta Warmup=0
UNET ZTol=0
UNET ZSATol=0
UNET MxIter=0
UNET MaxInSteps=0
UNET DtIC=0
UNET DtMin=0
UNET MaxCRTS=0
UNET WFStab=0
UNET SFStab=0
UNET WFX=0
UNET SFX=0
UNET DSS MLevel=0
UNET DZMax Abort=0
UNET Convert EG Bridges=0
UNET Use Existing IB Tables=0
UNET Froude Limit=0
UNET Froude Power=0
Write IC File=0
Echo Input=False
Echo Output=False
Write Detailed=0

--- HrsCrk.f01 (steady flow) ---

Flow Title=NFF Regression Equation
Program Version=4.00
Number of Profiles=1
Profile Names=P100yr
River Rch & RM=HrsCrk,Main      ,18820.4
885.6909
River Rch & RM=HrsCrk,Main      ,18098.6
894.6682
River Rch & RM=HrsCrk,Main      ,17682.8
1002.064
River Rch & RM=HrsCrk,Main      ,16425.8
1093.338
River Rch & RM=HrsCrk,Main      ,14428.2
1167.979
River Rch & RM=HrsCrk,Main      ,14032
1263.216
River Rch & RM=HrsCrk,Main      ,12848.8
1328.105
River Rch & RM=HrsCrk,Main      ,10435.4
1453.515
River Rch & RM=HrsCrk,Main      ,8061.7
1614.526
River Rch & RM=HrsCrk,Main      ,7668.7
1735.756
River Rch & RM=HrsCrk,Main      ,2084.6
1927.858
River Rch & RM=HrsCrk,Main      ,171.3
2069.518
Boundary for River Rch & Prof#=HrsCrk,Main      ,1
Up Type=0
Dn Type=3
Dn Slope=0.025883

--- HrsCrk.g01 (geometry) ---

Geom Title=USGS 3m DEM
Program Version=4.10

River Reach=HrsCrk          ,Main
Reach XY= 30
     1839018.643      327774.782     1838605.748      327746.371
     1838194.887      327477.788     1835827.415      326668.838
     1835571.555      326441.314     1835387.147      325966.617
     1834982.127      325781.206     1834146.454      324913.052
     1833835.885      324127.997     1833607.556      323887.644
     1833055.116      323741.357     1832082.904      323198.322
     1831484.036      323177.562     1830715.272      322426.253
     1830104.595      322250.472     1829832.459      321646.305
     1829881.939      321296.045     1829513.449       321061.67
     1829573.174      320523.655     1829141.053      320587.711
     1828885.845      319984.847      1828276.47      319814.274
     1827979.299      319354.772     1827697.956      319484.199
     1827587.944      319044.347     1827090.542      318847.474
     1826851.991      318566.878     1826336.366      318503.076
     1826257.019      318338.469     1826363.255      317834.147

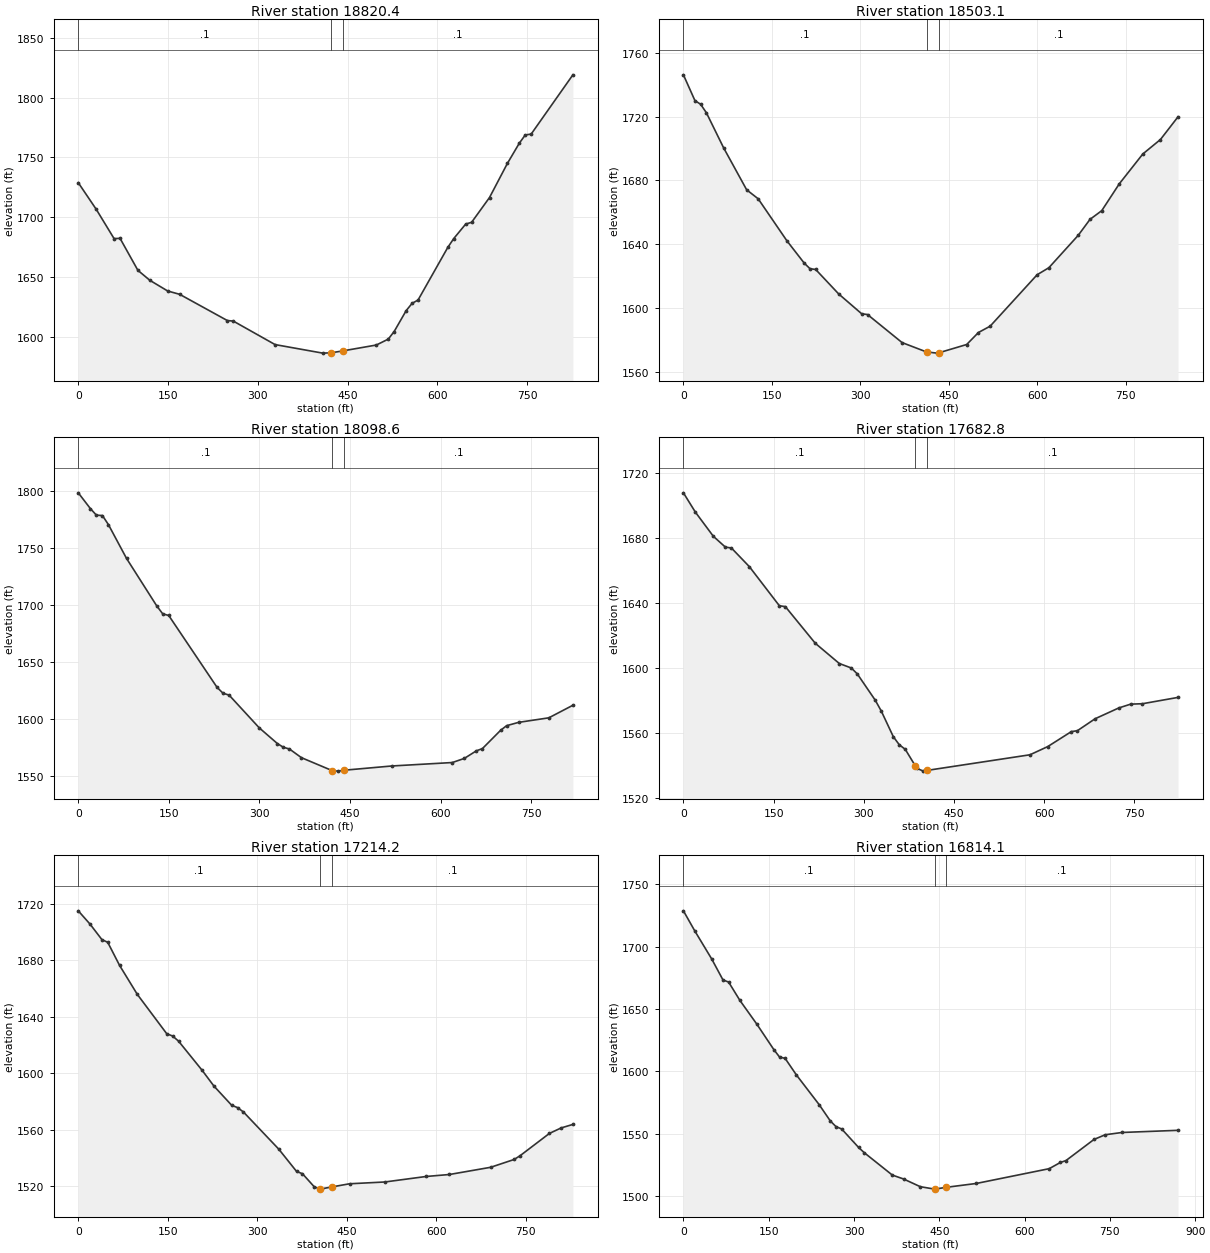
Type RM Length L Ch R = 1 ,18820.4 ,319,317.4,316.7
XS GIS Cut Line= 3
     1839094.247      327355.343     1838987.115      327687.205
     1838941.563      328162.704
#Sta/Elev= 30
       0 1728.92    29.9 1706.78    59.8 1682.22    69.8 1682.42    99.6 1655.72
   119.6 1647.36   149.4 1638.44   169.4 1635.67   249.1 1613.74     259 1613.31
   328.8 1593.67   408.4 1586.53   422.5 1586.79   442.5 1588.44     498  1593.3
   517.9 1598.23   527.8  1604.6   547.8    1622   557.7 1628.11   567.7  1630.9
   617.4 1674.87   627.4 1682.29   647.3 1694.36   657.2 1695.83   687.1 1716.55
   716.9 1744.98   736.8 1761.87   746.8  1768.8   756.7 1769.55   826.4 1819.05
#Mann= 3 , 0 , 0
       0      .1       0   422.5    .045       0   442.5      .1       0
Bank Sta=422.5,442.5
XS Rating Curve= 0 ,0
Exp/Cntr=0.3,0.1

Type RM Length L Ch R = 1 ,18503.1 ,393.2,404.2,414.3
XS GIS Cut Line= 3
      1838717.42      327279.423     1838688.084      327638.932
     1838674.848      328116.353
#Sta/Elev= 30
       0 1746.16    19.5 1730.03    29.2 1727.71      39 1722.36    68.2  1700.4
   107.2 1674.16   126.7 1668.54   175.5 1642.18   204.7 1628.28   214.5 1624.77
   224.2 1624.27   263.2 1608.94   302.2 1596.52     312 1596.07   370.6  1578.5
   412.4 1572.58   430.4  1571.9   432.4 1572.06   480.1  1577.3     500 1584.81
   519.9 1588.79   599.5 1620.98   619.4 1625.38   669.2 1645.69   689.1 1655.66
     709  1661.1   738.8 1677.95   778.6  1696.6   808.5 1705.66   838.3 1719.89
#Mann= 3 , 0 , 0
       0      .1       0   412.4    .045       0   432.4      .1       0
Bank Sta=412.4,432.4
XS Rating Curve= 0 ,0
Exp/Cntr=0.3,0.1

Type RM Length L Ch R = 1 ,18098.6 ,421,415.7,410.5
XS GIS Cut Line= 3
     1838549.045      327166.646     1838375.487      327537.541
     1838206.214      327910.454
#Sta/Elev= 30
       0 1798.34      20 1784.57      30 1778.77      40 1778.42    49.9  1770.5
    79.9 1740.86   129.8 1699.35   139.8  1692.3   149.8 1690.83   229.7 1627.92
   239.7 1622.66   249.7 1621.08   299.6 1592.39   329.6 1578.63   339.6 1575.31
   349.6 1573.84   369.5 1566.22   420.7  1554.8   429.5 1554.42   440.7 1555.24
   519.4 1558.94   619.3 1561.95   639.2 1565.56   659.2 1572.22   669.2 1574.18
   699.2 1590.14   709.2 1594.24   729.1 1597.16   779.1 1601.13     819 1612.16
#Mann= 3 , 0 , 0
       0      .1       0   420.7    .045       0   440.7      .1       0
Bank Sta=420.7,440.7
XS Rating Curve= 0 ,0
Exp/Cntr=0.3,0.1

Type RM Length L Ch R = 1 ,17682.8 ,459.9,468.2,479.5
XS GIS Cut Line= 3
     1838072.609      327015.026     1837984.027      327414.085
     1837888.683      327816.568
#Sta/Elev= 30
       0 1708.04    19.9 1696.14    49.8 1681.24    69.8 1674.58    79.8 1674.06
   109.7 1662.53   159.5 1638.48   169.5 1637.92   219.3 1615.33   259.2 1602.88
   279.2 1600.11   289.1 1596.47     319 1580.25     329 1573.57     349 1557.78
   358.9 1552.82   368.9 1549.98   385.3 1539.97   388.8 1538.21   398.8 1536.57
   405.3 1537.03   576.2 1546.64   605.7 1551.68   645.1 1560.94     655 1561.46
   684.5 1568.84   723.9  1575.5   743.6 1577.84   763.3  1578.1   822.4    1582
#Mann= 3 , 0 , 0
       0      .1       0   385.3    .045       0   405.3      .1       0
Bank Sta=385.3,405.3
XS Rating Curve= 0 ,0
Exp/Cntr=0.3,0.1

Type RM Length L Ch R = 1 ,17214.2 ,407.4,400.2,389.9
XS GIS Cut Line= 3
     1837768.548      326939.574     1837553.708      327295.026
      1837300.48      327622.235
#Sta/Elev= 30
       0 1714.98    19.8 1705.52    39.6 1694.59    49.4 1692.66    69.2 1676.33
    98.9  1655.8   148.3 1627.88   158.2 1626.25   168.1 1622.62   207.7 1601.91
   227.4 1590.78   257.1  1577.2     267 1575.52   276.9 1572.41   336.2 1546.03
   365.9  1530.3   375.8 1528.66   395.6 1519.38   405.3 1517.75   425.3 1519.33
   454.7 1521.54   513.8 1522.81   582.8  1526.7   622.2 1528.12   691.2 1533.22
   730.6 1538.77   740.4 1541.37   789.7 1557.22   809.4 1561.12   829.1 1563.61
#Mann= 3 , 0 , 0
       0      .1       0   405.3    .045       0   425.3      .1       0
Bank Sta=405.3,425.3
XS Rating Curve= 0 ,0
Exp/Cntr=0.3,0.1

Type RM Length L Ch R = 1 ,16814.1 ,381.7,387.9,398
XS GIS Cut Line= 3
     1837352.697      326706.276      1837231.59      327000.394
     1837095.112      327535.102
#Sta/Elev= 30
       0 1728.86    19.9 1712.82    49.7 1690.29    69.6 1673.41    79.5 1671.73
    99.4 1656.97   129.2 1637.92     159 1617.58     169 1611.63   178.9 1610.51
   198.8 1597.17   238.6  1573.5   258.4 1560.31   268.4 1555.77   278.3 1553.91
   308.1 1539.08   318.1 1534.85   367.4 1516.92   387.1  1513.8   416.6 1507.61
   441.9 1505.65   461.9 1507.08   515.2  1510.2   643.3 1522.05     663 1527.04
   672.8 1528.55   722.1  1545.5   741.8 1549.26   771.4 1551.09   869.9 1552.82
#Mann= 3 , 0 , 0
       0      .1       0   441.9    .045       0   461.9      .1       0
Bank Sta=441.9,461.9
XS Rating Curve= 0 ,0
Exp/Cntr=0.3,0.1

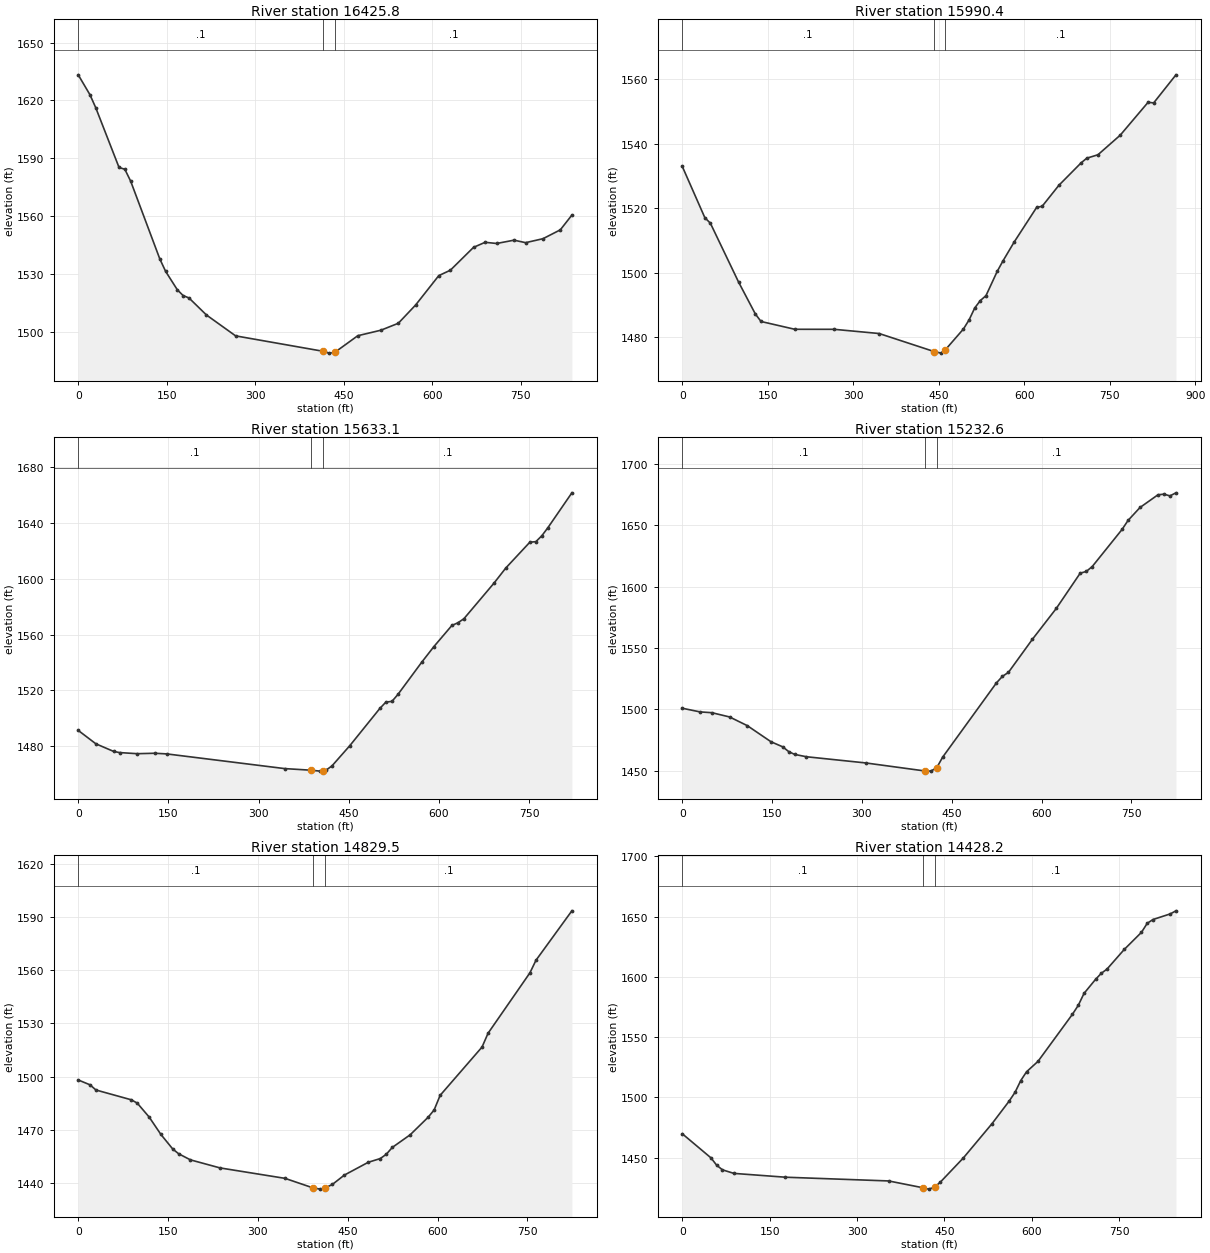
Type RM Length L Ch R = 1 ,16425.8 ,442.6,435.4,423.7
XS GIS Cut Line= 3
     1837028.763      326689.685     1836824.801      327062.388
     1836573.323      327388.684
#Sta/Elev= 30
       0 1633.32    19.8 1623.03    29.6 1616.32    69.2 1585.22      79  1584.3
    88.9 1578.11   138.3 1537.75   148.2 1531.26     168 1521.73   177.8 1518.74
   187.7  1517.5   217.4 1508.64   266.8 1497.81   414.9 1489.82   424.9 1488.85
   434.9 1489.25   473.9 1497.89   513.1 1500.75   542.6 1504.35     572 1513.86
   611.2 1529.09   630.8 1531.89   670.1 1543.76   689.7 1546.38   709.3 1545.77
   738.7 1547.49   758.4 1546.19   787.8 1548.25   817.2 1552.85   836.8  1560.5
#Mann= 3 , 0 , 0
       0      .1       0   414.9    .045       0   434.9      .1       0
Bank Sta=414.9,434.9
XS Rating Curve= 0 ,0
Exp/Cntr=0.3,0.1

Type RM Length L Ch R = 1 ,15990.4 ,349.1,357.3,367.1
XS GIS Cut Line= 3
     1836551.081       326504.43     1836416.517      327121.502
     1836470.197      327349.996
#Sta/Elev= 30
       0  1532.9    39.5 1517.07    49.3 1515.33    98.7 1497.14   128.3 1487.21
   138.2 1484.92   197.4 1482.51   266.4  1482.5   345.4  1481.2   441.7 1475.63
   453.9 1475.13   461.7 1476.18   493.4 1482.61   503.3 1485.42   513.2 1489.11
     523  1491.4   532.9 1492.91   552.6 1500.42   562.5  1503.6   582.2 1509.46
   621.7  1520.2   631.6  1520.6   660.9 1527.08     700 1534.04   709.8 1535.46
   729.4 1536.52   768.5 1542.58   817.4 1552.76   827.2 1552.57   866.3 1561.26
#Mann= 3 , 0 , 0
       0      .1       0   441.7    .045       0   461.7      .1       0
Bank Sta=441.7,461.7
XS Rating Curve= 0 ,0
Exp/Cntr=0.3,0.1

Type RM Length L Ch R = 1 ,15633.1 ,397.1,400.3,406.3
XS GIS Cut Line= 3
      1836341.94      326474.339     1836123.552        326823.7
     1835873.137      327147.152
#Sta/Elev= 30
       0 1491.21    29.4 1481.57    58.9 1476.12    68.7 1475.29    98.1 1474.49
   127.5  1474.8   147.1 1474.34   343.3 1463.79   387.5 1462.62   402.2 1461.97
   407.5 1462.32     412 1462.61     422 1465.69   451.9 1480.33   501.8 1507.03
   511.8 1511.55   521.8 1512.03   531.7 1516.99   571.6  1540.3   591.6 1551.38
   621.5 1566.54   631.5 1568.47   641.5 1571.36   691.4 1596.85   711.3 1607.84
   751.2 1626.32   761.2  1626.7   771.2 1630.99   781.2 1636.72   821.1 1661.76
#Mann= 3 , 0 , 0
       0      .1       0   387.5    .045       0   407.5      .1       0
Bank Sta=387.5,407.5
XS Rating Curve= 0 ,0
Exp/Cntr=0.3,0.1

Type RM Length L Ch R = 1 ,15232.6 ,391.8,403,413.5
XS GIS Cut Line= 3
      1836048.74      326303.483     1835785.232      326623.874
     1835481.296      326898.491
#Sta/Elev= 30
       0  1500.9    29.6 1497.92    49.4 1497.27      79 1493.79   108.6 1486.69
   148.2 1473.55   167.9 1469.38   177.8  1465.5   187.7 1463.24   207.4 1461.33
   306.2 1456.29   404.8 1449.75   414.8  1449.6   424.8 1452.21   434.8 1460.98
   524.7  1521.6   534.7 1526.94   544.7 1530.15   584.7 1557.14   624.6  1582.3
   664.6  1611.1   674.6 1612.47   684.6 1616.45   734.5 1646.78   744.5 1654.12
   764.5 1664.69   794.5 1675.05   804.5 1675.54   814.5 1674.15   824.5 1676.64
#Mann= 3 , 0 , 0
       0      .1       0   404.8    .045       0   424.8      .1       0
Bank Sta=404.8,424.8
XS Rating Curve= 0 ,0
Exp/Cntr=0.3,0.1

Type RM Length L Ch R = 1 ,14829.5 ,407.9,401.3,389.1
XS GIS Cut Line= 3
        1835927.      326170.952     1835545.881      326333.536
     1835144.767      326418.447
#Sta/Elev= 30
       0 1498.06    19.7 1495.31    29.6 1492.39    88.8 1486.84    98.6 1484.97
   118.4 1477.14   138.1 1467.27   157.8 1459.08   167.7 1456.37   187.4 1452.93
   236.8 1448.38   345.3 1442.49   392.4 1437.06   404.5  1436.4   412.4  1437.1
   424.4 1439.04   444.4 1444.32   484.4 1451.57   504.4 1453.66   514.4 1456.06
   524.4 1459.93   554.4  1467.1   584.4 1477.02   594.4 1481.13   604.4 1489.37
   674.4 1516.66   684.4 1524.43   754.4  1558.6   764.4 1565.65   824.4 1593.59
#Mann= 3 , 0 , 0
       0      .1       0   392.4    .045       0   412.4      .1       0
Bank Sta=392.4,412.4
XS Rating Curve= 0 ,0
Exp/Cntr=0.3,0.1

Type RM Length L Ch R = 1 ,14428.2 ,402.3,396,391.4
XS GIS Cut Line= 3
     1835697.904      325709.191     1835393.829      325974.282
     1835087.054      326295.316
#Sta/Elev= 30
       0 1469.87    49.2 1449.88      59 1443.76    68.9 1439.95    88.6 1436.99
   177.1 1433.82   354.2 1430.72   413.3 1425.04   423.1 1423.93     433  1425.6
   442.9 1429.71   482.4 1449.79   531.7 1478.28   561.3 1497.14   571.2 1504.31
     581 1514.02   590.9 1521.32   610.6 1529.98   669.8 1569.12   679.7 1576.44
   689.6 1586.39   709.3 1597.97   719.2 1603.04     729 1606.53   758.6 1622.83
   788.2 1637.07   798.1 1644.57     808  1647.7   837.6 1652.36   847.4 1654.91
#Mann= 3 , 0 , 0
       0      .1       0   413.3    .045       0     433      .1       0
Bank Sta=413.3,433
XS Rating Curve= 0 ,0
Exp/Cntr=0.3,0.1

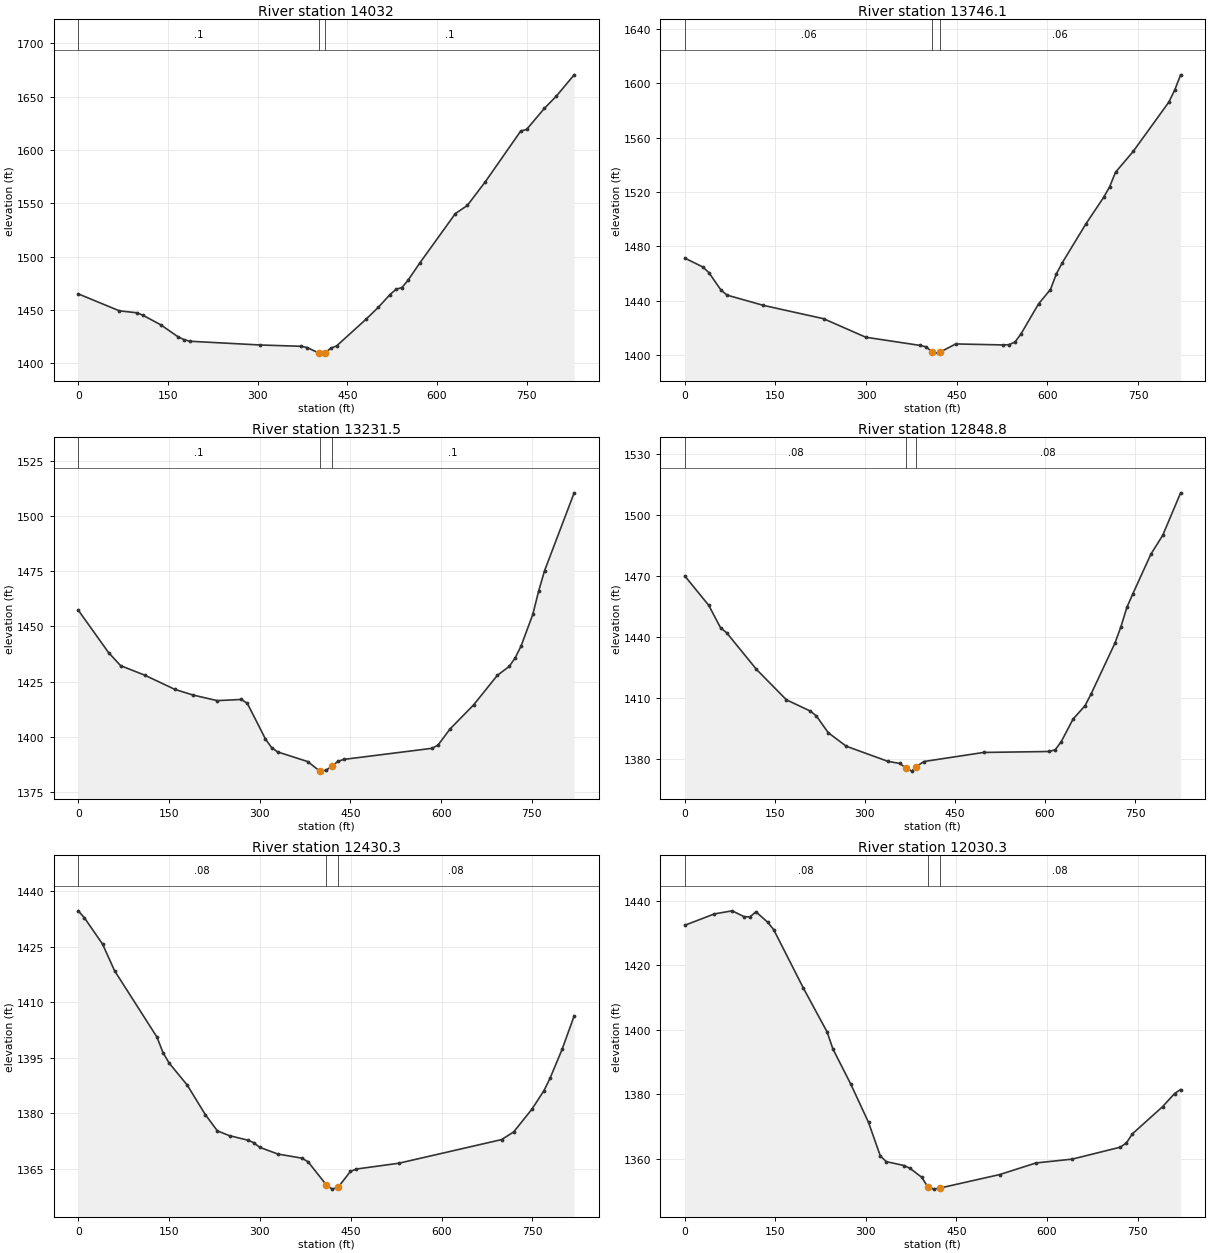
Type RM Length L Ch R = 1 ,14032   ,279.7,285.8,292.1
XS GIS Cut Line= 3
     1835267.879      325472.033     1835028.707      325819.958
     1834814.105      326166.087
#Sta/Elev= 30
       0 1464.96    68.7 1449.06    98.2 1447.21     108 1444.93   137.5 1436.07
   166.9  1424.7   176.7 1422.03   186.6 1420.52   304.4 1417.01   373.1 1415.78
   382.9 1414.58   402.6 1409.37   412.4 1409.52   422.2 1413.91   432.1 1416.14
   481.8 1441.44   501.7 1452.28   521.5 1464.38   531.5 1469.23   541.4 1470.96
   551.3 1477.57   571.2 1493.92   630.8 1540.36   650.7 1547.94   680.5 1569.91
   740.1 1617.81     750 1619.34   779.8 1639.17   799.7 1650.59   829.5 1670.57
#Mann= 3 , 0 , 0
       0      .1       0   402.6    .045       0   412.4      .1       0
Bank Sta=402.6,412.4
XS Rating Curve= 0 ,0
Exp/Cntr=0.3,0.1

Type RM Length L Ch R = 1 ,13746.1 ,511.1,514.6,516.6
XS GIS Cut Line= 3
     1835178.295      325329.252     1834862.271      325589.189
     1834558.115      325865.842
#Sta/Elev= 30
       0 1471.36    29.9 1464.81    39.9 1460.66    59.9 1447.81    69.9 1444.12
   129.7 1436.62   229.6 1426.78   299.4 1413.16   389.2 1407.14   399.2  1406.1
   409.2 1402.38     419 1401.46   421.5 1402.02   448.4 1408.22   526.7 1407.49
   536.4 1407.68   546.2 1409.58     556 1415.39   585.4 1437.74     605 1448.23
   614.8 1459.74   624.6 1467.95   663.7 1496.53   693.1 1516.06   702.9 1523.78
   712.7 1534.49     742 1549.86   800.8 1586.03   810.6 1594.91   820.4 1606.14
#Mann= 3 , 0 , 0
       0     .06       0   409.2    .045       0   421.5     .06       0
Bank Sta=409.2,421.5
XS Rating Curve= 0 ,0
Exp/Cntr=0.3,0.1

Type RM Length L Ch R = 1 ,13231.5 ,389.1,382.7,377.8
XS GIS Cut Line= 3
     1834851.389      324988.845     1834511.319      325216.629
     1834186.018      325467.151
#Sta/Elev= 30
       0 1457.36    49.9 1438.23    69.9 1432.28   109.8 1427.98   159.7 1421.54
   189.7 1418.99   229.6 1416.46   269.5 1416.99   279.5  1415.2   309.5 1399.06
   319.5 1395.25   329.4 1393.27   379.4 1388.87   399.3 1384.56   409.3 1384.94
   419.3 1386.75   428.9 1388.94   438.6 1389.85   585.3  1394.9     595  1396.4
   614.6 1403.61   653.7 1414.55   692.8 1427.88   712.4 1431.91   722.1 1435.68
   731.9 1441.03   751.5 1455.45   761.2 1466.04     771 1475.27   819.9 1510.48
#Mann= 3 , 0 , 0
       0      .1       0   399.3    .045       0   419.3      .1       0
Bank Sta=399.3,419.3
XS Rating Curve= 0 ,0
Exp/Cntr=0.3,0.1

Type RM Length L Ch R = 1 ,12848.8 ,405.2,418.5,431.7
XS GIS Cut Line= 3
     1834467.259      324695.417       1834190.8      325009.044
     1833932.009      325324.381
#Sta/Elev= 30
       0 1470.05    39.8 1455.63    59.7 1444.49    69.7 1442.11   119.4 1424.08
   169.2 1409.13     209 1403.58     219 1401.24   238.9 1392.96   268.8  1386.3
   338.4 1378.83   358.4 1377.78   368.3 1375.54   378.3 1374.02   384.6 1376.01
   398.2 1378.74   497.7 1383.21   607.1 1383.68   617.1 1384.54     627 1388.46
   646.9 1399.67   666.8 1406.22   676.8 1411.96   716.6 1437.02   726.5 1445.01
   736.5 1454.62   746.4 1461.28   776.3 1480.68   796.2 1490.07     826 1510.94
#Mann= 3 , 0 , 0
       0     .08       0   368.3    .045       0   384.6     .08       0
Bank Sta=368.3,384.6
XS Rating Curve= 0 ,0
Exp/Cntr=0.3,0.1

Type RM Length L Ch R = 1 ,12430.3 ,399.6,399.9,397.8
XS GIS Cut Line= 3
     1834402.929       324492.36     1834014.217      324621.176
     1833625.506      324749.992
#Sta/Elev= 30
       0 1434.76      10 1432.88      40 1425.77    59.9 1418.53   129.8 1400.61
   139.8 1396.41   149.8  1393.6   179.8 1387.62   209.7 1379.62   229.7  1375.2
   249.7 1373.91   279.7  1372.7   289.6 1372.03   299.6 1370.75   329.6 1368.94
   369.6 1367.81   379.5 1366.84   409.5 1360.62   419.5 1359.44   429.5 1360.02
   449.4 1364.23   459.4 1364.88   529.4 1366.45   699.2 1372.85   719.1 1374.92
   749.1 1381.05   769.1 1386.09     779 1389.39     799 1397.24     819 1406.32
#Mann= 3 , 0 , 0
       0     .08       0   409.5    .045       0   429.5     .08       0
Bank Sta=409.5,429.5
XS Rating Curve= 0 ,0
Exp/Cntr=0.3,0.1

Type RM Length L Ch R = 1 ,12030.3 ,406.9,391.8,378.7
XS GIS Cut Line= 3
     1834253.269        324129.7     1833860.133      324253.763
     1833483.725      324413.795
#Sta/Elev= 30
       0  1432.4    49.1 1435.92    78.5 1436.87    98.2 1435.06     108    1435
   117.8 1436.57   137.4 1433.33   147.2 1431.05   196.3 1412.99   235.6 1399.41
   245.4 1394.06   274.8 1383.26   304.3 1371.35   323.9 1360.96   333.7  1359.2
   363.2 1357.99     373 1357.13   392.6 1354.33   402.2 1351.46   412.2 1350.68
   422.2    1351     522 1355.21   581.8 1358.79   641.7 1359.97   721.5 1363.68
   731.5 1364.99   741.4  1367.8   791.3  1376.2   811.3 1380.29   821.3 1381.52
#Mann= 3 , 0 , 0
       0     .08       0   402.2    .045       0   422.2     .08       0
Bank Sta=402.2,422.2
XS Rating Curve= 0 ,0
Exp/Cntr=0.3,0.1

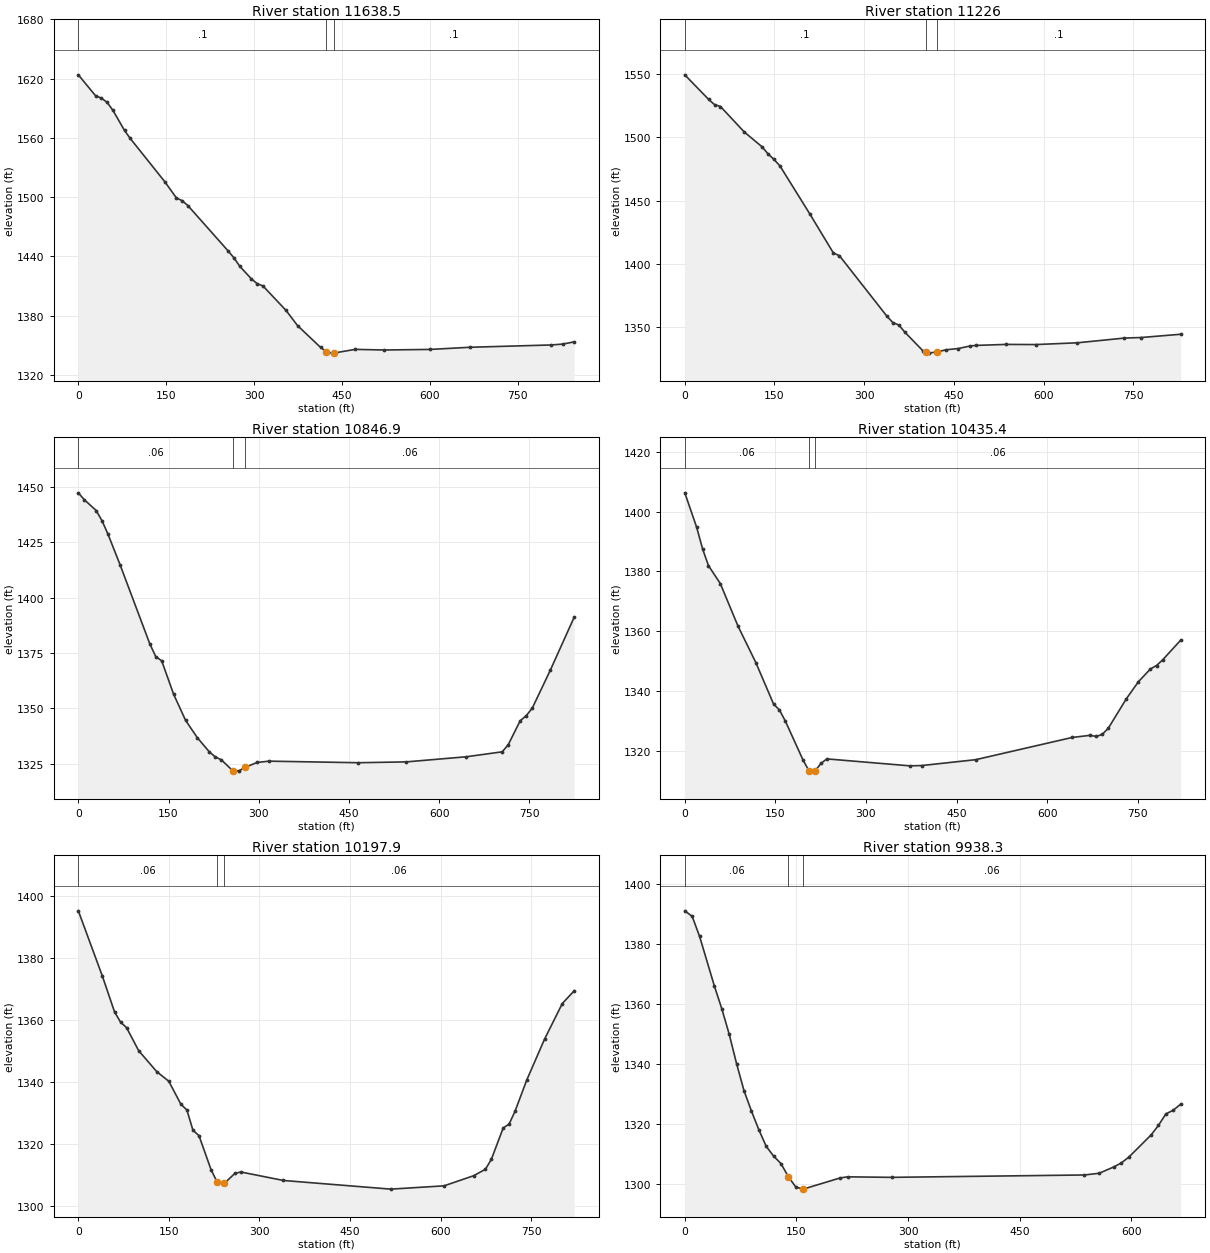
Type RM Length L Ch R = 1 ,11638.5 ,420.8,412.5,404.8
XS GIS Cut Line= 3
      1833974.83      323648.383     1833672.827      323916.245
     1833405.156      324268.591
#Sta/Elev= 30
       0 1623.86    29.5 1602.61    39.4 1600.27    49.2 1595.89    59.1 1587.82
    78.8 1567.51    88.6  1559.4   147.7 1515.45   167.4 1499.11   177.2 1496.34
   187.1  1491.3     256 1445.22   265.8 1438.24   275.7 1429.77   295.4 1417.13
   305.2 1412.28   315.1 1409.98   354.4 1385.23   374.1 1369.82   413.5 1347.66
   423.3 1343.28   433.2  1341.9   436.2 1341.99   472.5 1345.71   521.7 1345.07
   600.3 1345.66   669.2 1347.85   806.8 1350.17   826.5 1351.04   846.2  1353.3
#Mann= 3 , 0 , 0
       0      .1       0   423.3    .045       0   436.2      .1       0
Bank Sta=423.3,436.2
XS Rating Curve= 0 ,0
Exp/Cntr=0.3,0.1

Type RM Length L Ch R = 1 ,11226   ,377.5,379,380.5
XS GIS Cut Line= 3
     1833424.758      323413.377     1833174.586      324094.871
     1833111.868      324176.946
#Sta/Elev= 30
       0 1549.44    39.8 1530.04    49.7 1525.89    59.7 1524.39    99.4  1504.3
   129.3 1492.49   139.2 1486.95   149.2 1482.55   159.1 1477.46   208.8 1439.71
   248.6 1408.55   258.6 1406.48   338.1  1358.6   348.1 1353.55     358 1351.69
     368 1346.03   397.8 1331.49   402.6  1330.5   407.7 1329.44   422.6 1330.51
   437.6 1332.12   457.5 1333.09   477.3 1335.09   487.3 1335.54     537 1336.33
   586.7 1336.21   656.4  1337.6   735.4 1341.35   763.5 1341.78   829.3 1344.36
#Mann= 3 , 0 , 0
       0      .1       0   402.6    .045       0   422.6      .1       0
Bank Sta=402.6,422.6
XS Rating Curve= 0 ,0
Exp/Cntr=0.3,0.1

Type RM Length L Ch R = 1 ,10846.9 ,410.8,411.5,412.2
XS GIS Cut Line= 3
     1833047.494      323422.497     1832880.515      323803.406
     1832710.328      324174.768
#Sta/Elev= 30
       0 1447.26     9.9 1444.15    29.7 1439.28    39.6 1434.56    49.5 1428.48
    69.3 1414.89   118.8 1379.18   128.7 1373.41   138.6 1371.49   158.4 1356.46
   178.2 1344.72     198 1336.77   217.8 1330.45   227.8 1328.15   237.7 1326.86
   257.5 1321.75   267.4 1321.93   277.3 1323.45   297.1 1325.65   316.9 1326.25
   465.7 1325.54   545.4 1325.92   645.1 1328.23   704.8 1330.46   714.8 1333.67
   734.7 1344.48   744.7 1346.75   754.7 1350.14   784.6 1367.17   824.4 1391.15
#Mann= 3 , 0 , 0
       0     .06       0   257.5    .045       0   277.3     .06       0
Bank Sta=257.5,277.3
XS Rating Curve= 0 ,0
Exp/Cntr=0.3,0.1

Type RM Length L Ch R = 1 ,10435.4 ,236.2,237.4,238.7
XS GIS Cut Line= 3
     1832667.096       323287.48     1832491.604      323659.833
     1832298.615      324020.889
#Sta/Elev= 30
       0 1406.26    19.6 1394.77    29.4 1387.55    39.2 1381.92    58.8 1375.93
    88.2 1361.66   117.6 1349.54     147 1335.66   156.8 1333.66   166.6 1329.92
   195.9  1316.9   205.8 1313.27   215.6 1313.24   215.9 1313.32   225.4 1315.82
   235.2 1317.33   372.4 1315.01     392  1315.1   481.5 1317.06   641.3 1324.49
   671.2 1325.21   681.2 1324.83   691.2 1325.52   701.2 1327.57   731.2 1337.45
   751.1 1343.12   771.1 1347.41   781.1 1348.54   791.1  1350.4     821 1356.99
#Mann= 3 , 0 , 0
       0     .06       0   205.8    .045       0   215.9     .06       0
Bank Sta=205.8,215.9
XS Rating Curve= 0 ,0
Exp/Cntr=0.3,0.1

Type RM Length L Ch R = 1 ,10197.9 ,259.6,259.6,259.6
XS GIS Cut Line= 3
     1832478.146      323160.152     1832284.808      323521.242
     1832104.411      323891.147
#Sta/Elev= 30
       0 1395.24      40 1374.08    59.9 1362.67    69.9 1359.33    79.9 1357.55
    99.9 1350.13   129.9 1343.35   149.8 1340.26   169.8 1332.86   179.8 1330.97
   189.8 1324.46   199.8  1322.7   219.8 1311.73   229.8 1307.73   241.9 1307.33
   259.7 1310.61   269.7 1310.96   339.7 1308.24   517.4 1305.45   605.6 1306.51
   654.6 1309.77   674.2 1311.86     684 1315.08   703.6 1325.18   713.4 1326.45
   723.2 1330.58   742.8 1340.75   772.2 1353.89   801.5 1365.34   821.1 1369.43
#Mann= 3 , 0 , 0
       0     .06       0   229.8    .045       0   241.9     .06       0
Bank Sta=229.8,241.9
XS Rating Curve= 0 ,0
Exp/Cntr=0.3,0.1

Type RM Length L Ch R = 1 ,9938.3  ,300.9,288.8,276.8
XS GIS Cut Line= 2
     1832213.195        323107.3     1831899.041      323694.571
#Sta/Elev= 30
       0 1390.96     9.9 1389.13    19.9 1382.43    39.8 1365.88    49.7 1358.38
    59.6 1349.94    69.6 1340.06    79.5 1331.14    89.5 1324.36    99.4 1318.15
   109.4 1312.57   119.3 1309.36   129.2 1306.85   139.2 1302.45   149.1 1299.06
   158.5  1298.4     159 1298.36   208.8 1302.09   218.7 1302.45   278.3 1302.28
   536.8 1303.07   556.7 1303.65   576.6 1305.78   586.5 1307.12   596.4    1309
   626.3 1316.38   636.2 1319.56   646.1 1323.37   656.1 1324.62     666 1326.62
#Mann= 3 , 0 , 0
       0     .06       0   139.2    .045       0   158.5     .06       0
Bank Sta=139.2,158.5
XS Rating Curve= 0 ,0
Exp/Cntr=0.3,0.1

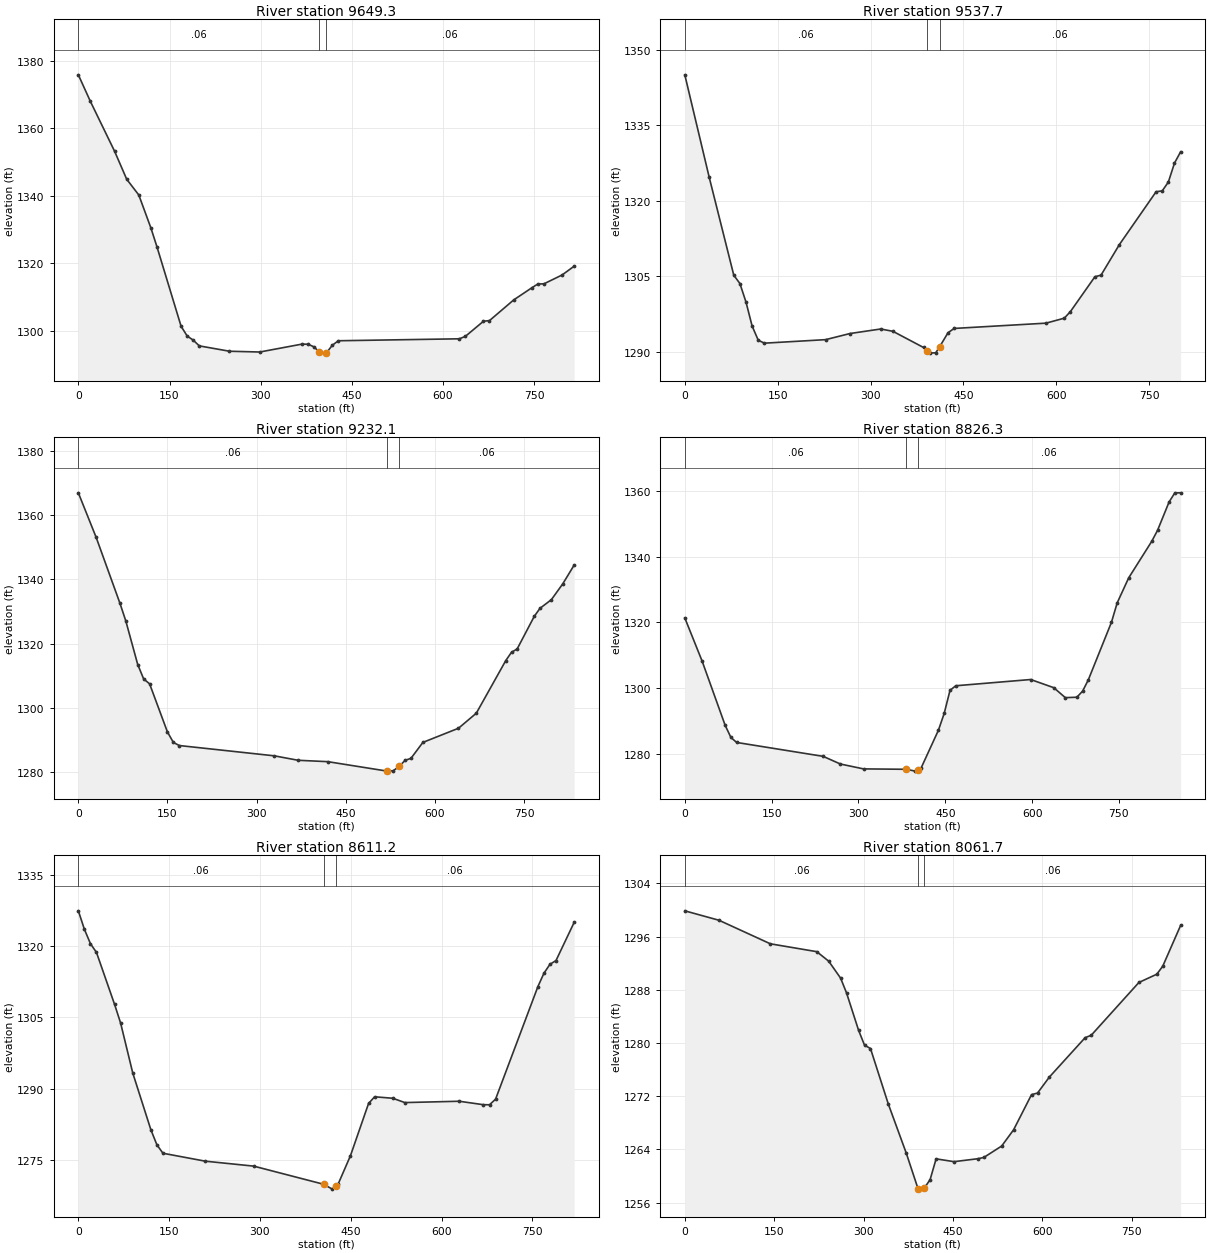
Type RM Length L Ch R = 1 ,9649.3  ,111.2,111.6,112
XS GIS Cut Line= 2
     1831888.797      322823.369     1831855.203      323638.492
#Sta/Elev= 30
       0 1375.89    19.9 1367.98    59.7  1353.2    79.6 1344.91    99.5 1340.24
   119.4 1330.46   129.3 1324.91   169.1 1301.29   179.1  1298.4     189 1297.19
     199 1295.48   248.7 1293.89   298.5 1293.66   368.1 1296.01   378.1 1295.96
     388 1295.17   396.6  1293.6   407.9 1293.33   417.9 1295.67   427.8    1297
   626.8 1297.58   636.7 1298.29   666.6 1302.79   676.5 1302.98   716.3 1309.11
   746.2 1312.72   756.1 1313.84   766.1 1313.89   795.9 1316.51   815.8 1319.12
#Mann= 3 , 0 , 0
       0     .06       0   396.6    .045       0   407.9     .06       0
Bank Sta=396.6,407.9
XS Rating Curve= 0 ,0
Exp/Cntr=0.3,0.1

Type RM Length L Ch R = 1 ,9537.7  ,292.6,305.5,318.4
XS GIS Cut Line= 2
     1831783.835      322818.121     1831738.351      323617.584
#Sta/Elev= 30
       0 1345.06    39.5 1324.64    79.1 1305.21      89 1303.55    98.9 1299.84
   108.7 1295.11   118.6 1292.28   128.5 1291.69   227.4 1292.39   266.9 1293.61
   316.4 1294.51   336.1 1294.05   385.6 1290.83   391.8 1290.12   395.4 1289.71
   405.3 1289.78   411.8 1291.02   425.1 1293.76     435 1294.62   583.3 1295.67
   612.9 1296.66   622.8 1297.97   662.4 1304.91   672.2 1305.21   701.9  1311.3
   761.2 1321.81   771.1 1321.98     781 1323.74   790.9 1327.51   800.8 1329.75
#Mann= 3 , 0 , 0
       0     .06       0   391.8    .045       0   411.8     .06       0
Bank Sta=391.8,411.8
XS Rating Curve= 0 ,0
Exp/Cntr=0.3,0.1

Type RM Length L Ch R = 1 ,9232.1  ,396.3,405.7,415.2
XS GIS Cut Line= 3
     1831748.847      322716.657     1831367.484      323314.943
     1831290.511      323412.908
#Sta/Elev= 30
       0 1366.85      30    1353      70 1332.54    79.9 1327.02    99.9 1313.51
   109.9 1309.02   119.9  1307.5   149.9 1292.54   159.9 1289.29   169.9 1288.33
   329.8 1285.13   369.7 1283.75   419.7 1283.32   519.6 1280.38     520 1280.38
   529.6 1280.48     540 1281.88   549.6 1283.72   559.6 1284.36   579.6  1289.3
   639.5  1293.7   669.5 1298.38   719.1 1314.74   728.7 1317.31   738.2 1318.34
     767 1328.47   776.6 1330.96   795.8 1333.66   814.9 1338.56   834.1  1344.4
#Mann= 3 , 0 , 0
       0     .06       0     520    .045       0     540     .06       0
Bank Sta=520,540
XS Rating Curve= 0 ,0
Exp/Cntr=0.3,0.1

Type RM Length L Ch R = 1 ,8826.3  ,219.6,215.1,210.6
XS GIS Cut Line= 2
     1831526.677      322627.439     1830835.106      323132.879
#Sta/Elev= 30
       0 1321.33    29.9 1308.19    69.7 1288.64    79.7 1284.92    89.6 1283.41
     239 1279.18   268.9 1276.84   308.8 1275.36   382.2 1275.24   398.4 1274.68
   402.2 1275.06   408.4 1275.69   438.2 1287.14   448.2 1292.29   458.2 1299.28
   468.1 1300.67   597.6 1302.57   637.5 1300.08   657.4 1297.05   677.3 1297.18
   687.3 1299.04   697.2  1302.5   737.1    1320     747  1325.9   766.9 1333.53
   806.8 1344.67   816.7 1347.98   836.7 1356.64   846.6 1359.39   856.6 1359.41
#Mann= 3 , 0 , 0
       0     .06       0   382.2    .045       0   402.2     .06       0
Bank Sta=382.2,402.2
XS Rating Curve= 0 ,0
Exp/Cntr=0.3,0.1

Type RM Length L Ch R = 1 ,8611.2  ,568,549.5,531
XS GIS Cut Line= 3
      1831357.14      322396.017     1831075.097      322692.905
     1830793.055      322989.793
#Sta/Elev= 30
       0 1327.45      10 1323.56      20 1320.53      30 1318.67    59.9 1307.72
    69.9 1303.77    89.9 1293.27   119.8 1281.32   129.8 1278.13   139.8 1276.36
   209.7 1274.69   289.6 1273.65   405.3 1269.82   419.5  1268.8   425.3 1269.48
   429.5 1269.97   449.4 1275.81   479.4 1286.85   489.4 1288.26   519.4 1287.95
   539.3 1287.04   629.2 1287.32   669.2 1286.59   679.2 1286.58   689.2 1287.76
   759.1 1311.48   769.1  1314.3     779 1316.18     789 1316.97     819 1325.02
#Mann= 3 , 0 , 0
       0     .06       0   405.3    .045       0   425.3     .06       0
Bank Sta=405.3,425.3
XS Rating Curve= 0 ,0
Exp/Cntr=0.3,0.1

Type RM Length L Ch R = 1 ,8061.7  ,378.1,393.1,408.4
XS GIS Cut Line= 3
     1830690.832      321998.178     1830627.936      322178.944
     1830613.504      322819.214
#Sta/Elev= 30
       0 1299.88    57.4 1298.46   143.6 1294.92   221.4 1293.74   241.4 1292.31
   261.4 1289.76   271.4 1287.52   291.5 1281.93   301.5 1279.68   311.5 1279.18
   341.5 1270.81   371.5 1263.46   391.5 1258.04   401.7 1258.19   411.5 1259.46
   421.6 1262.59   451.6 1262.17   491.6 1262.61   501.6  1262.8   531.6 1264.52
   551.6 1266.96   581.7 1272.25   591.7 1272.48   611.7  1274.9   671.7 1280.82
   681.7 1281.16   761.8 1289.11   791.8 1290.35   801.8 1291.55   831.8 1297.69
#Mann= 3 , 0 , 0
       0     .06       0   391.5    .045       0   401.7     .06       0
Bank Sta=391.5,401.7
XS Rating Curve= 0 ,0
Exp/Cntr=0.3,0.1