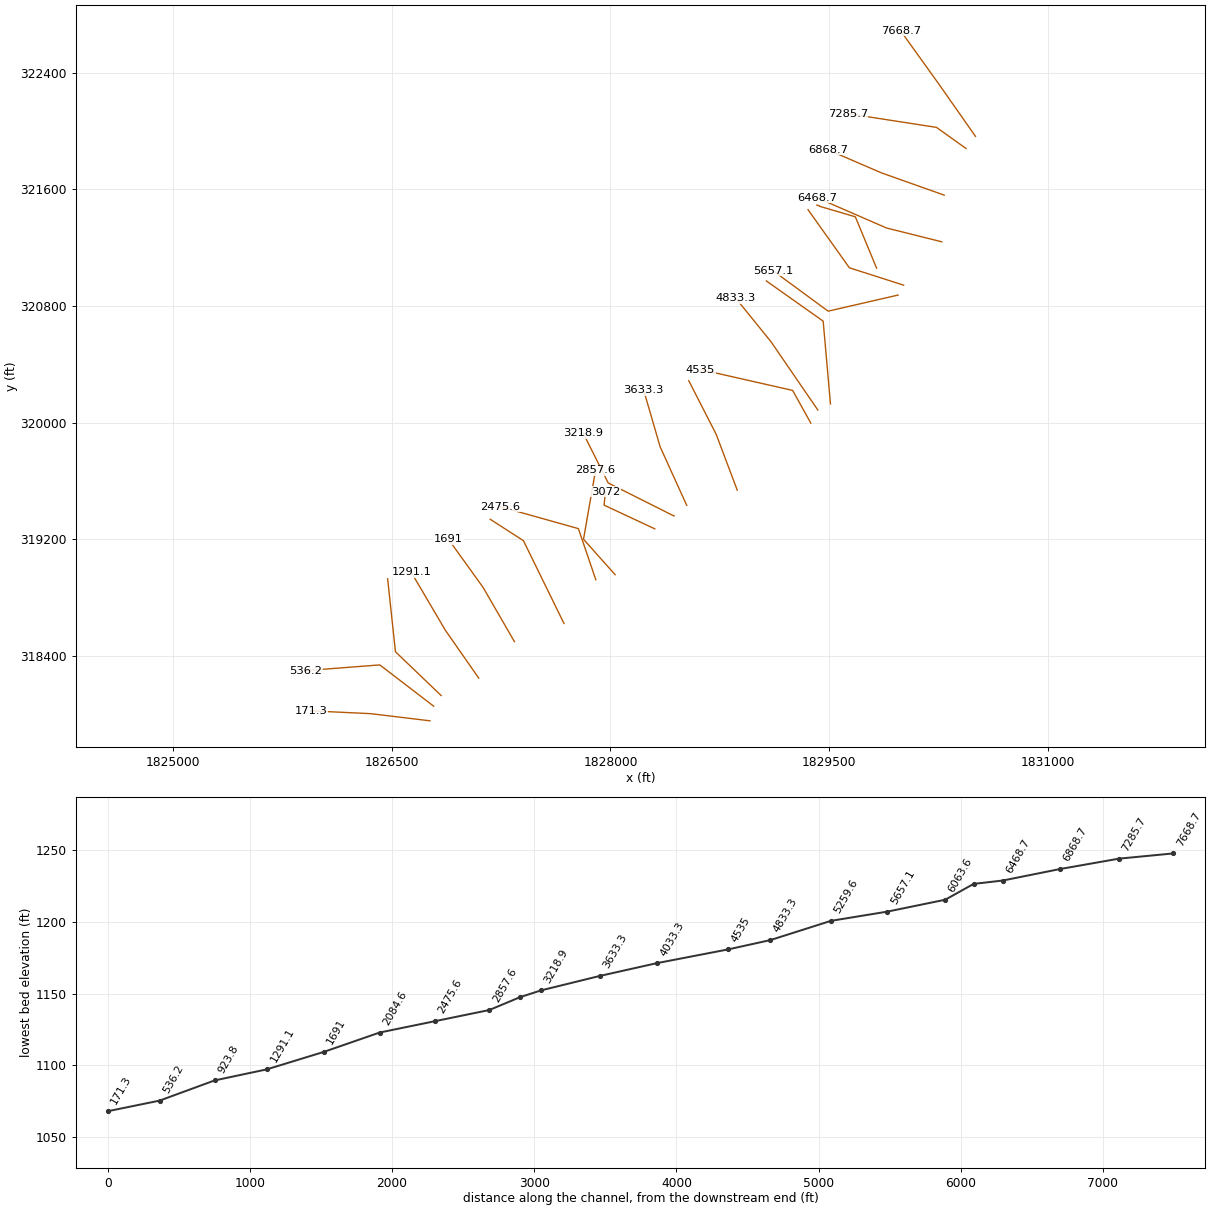
HEC-RAS study HrsCrk.prj: HrsCrk

--- HrsCrk.g01 (geometry) --- (continued)

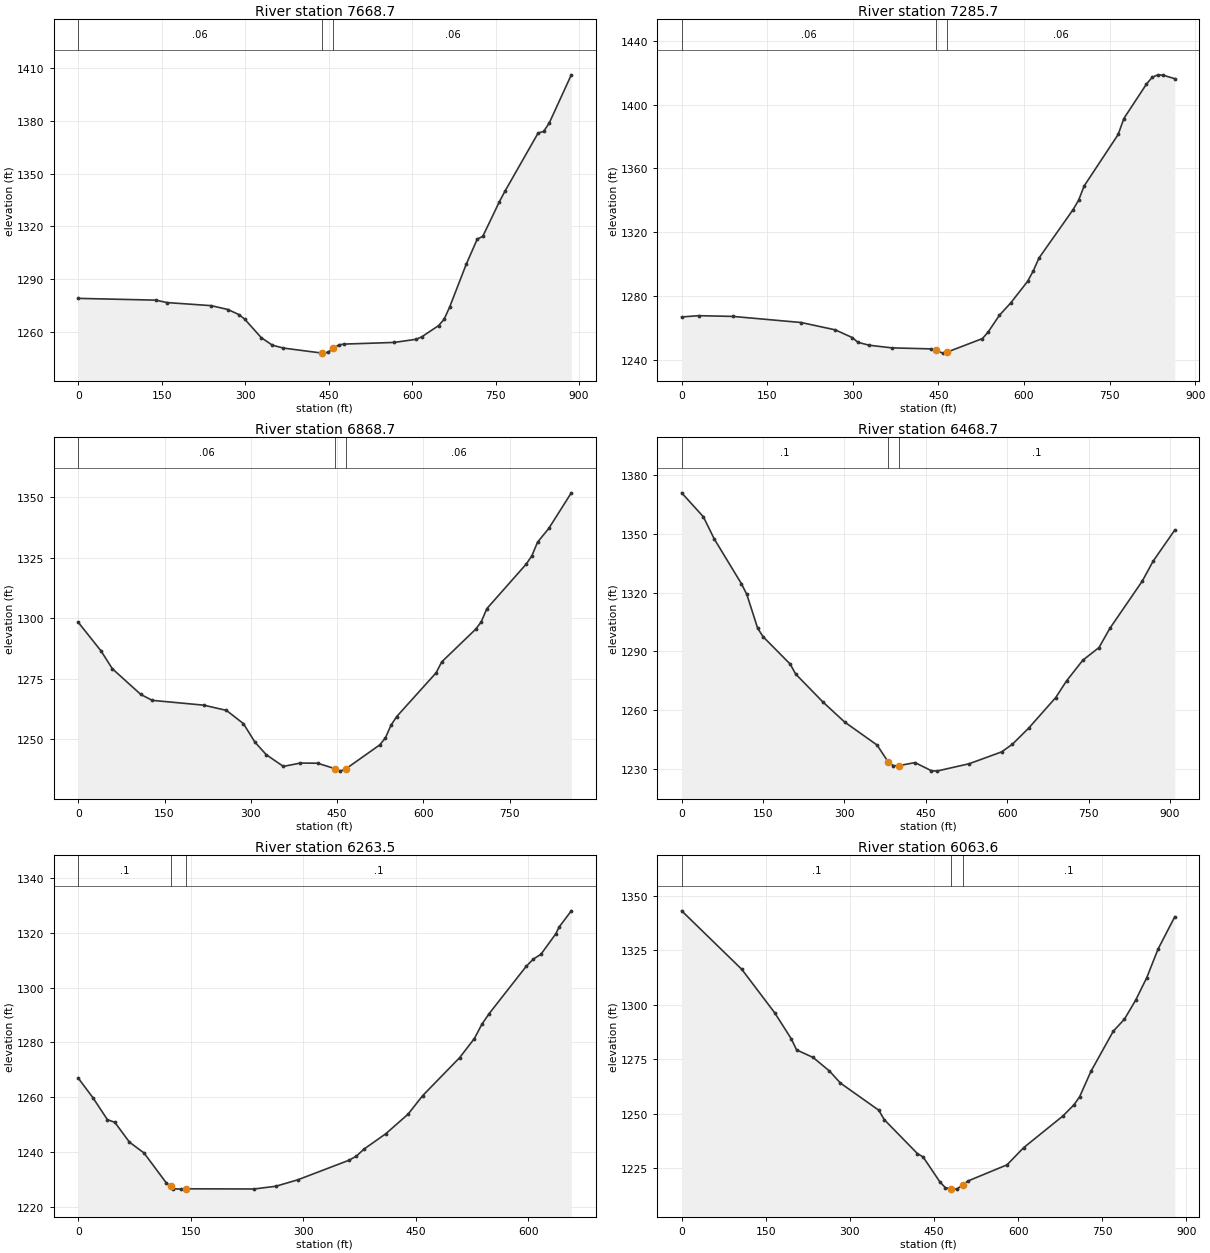
Type RM Length L Ch R = 1 ,7668.7  ,362.3,383,403.3
XS GIS Cut Line= 3
     1830501.562       321962.71     1830244.118      322329.973
     1829988.978      322685.387
#Sta/Elev= 30
       0 1278.99   139.5 1277.98   159.5  1276.6   239.2 1274.84   269.1 1272.64
     289 1269.72     299 1267.21   328.9 1256.64   348.8 1252.34   368.8 1250.69
   438.5 1247.81   448.5 1248.24   458.5  1250.5   468.4 1252.54   478.3 1252.96
   567.8  1253.9   607.6 1255.71   617.6 1257.16   647.4 1263.45   657.3 1267.01
   667.3 1273.96   697.1 1298.34     717 1312.75   726.9 1314.28   756.8 1334.04
   766.7 1339.97   826.4 1373.15   836.3 1374.07   846.2 1378.75     886 1406.28
#Mann= 3 , 0 , 0
       0     .06       0   438.5    .045       0   458.5     .06       0
Bank Sta=438.5,458.5
XS Rating Curve= 0 ,0
Exp/Cntr=0.3,0.1

Type RM Length L Ch R = 1 ,7285.7  ,421.4,416.9,410.9
XS GIS Cut Line= 3
     1830436.905      321879.528      1830233.89      322024.343
     1829626.188      322118.099
#Sta/Elev= 30
       0 1266.83    29.9 1267.63    89.8 1267.17   209.5 1263.34   269.2 1258.74
     299 1253.91   308.9 1250.94   328.7  1249.1   368.4 1247.44   437.8 1246.81
   445.9  1245.8   457.6 1244.15   465.9 1244.88   527.1 1253.26     537  1257.3
   556.8 1267.85   576.6 1275.58   606.4 1289.18   616.3 1295.76   626.2 1303.74
   685.8 1334.02   695.7 1340.01   705.6 1349.06   765.1 1381.27     775 1391.25
   814.7 1412.88   824.6 1417.06   834.5 1418.64   844.4 1418.35   864.3 1416.23
#Mann= 3 , 0 , 0
       0     .06       0   445.9    .045       0   465.9     .06       0
Bank Sta=445.9,465.9
XS Rating Curve= 0 ,0
Exp/Cntr=0.3,0.1

Type RM Length L Ch R = 1 ,6868.7  ,398.1,400,399.3
XS GIS Cut Line= 3
     1830287.253      321559.845     1829857.931      321712.117
     1829489.336      321870.994
#Sta/Elev= 30
       0  1298.4    39.6 1286.56    59.4 1279.16   108.9 1268.53   128.7 1266.11
   217.9 1264.13   257.5 1261.98   287.2 1256.48     307 1248.88   326.8 1243.66
   356.5 1238.81   386.2  1240.2   415.9 1240.13   445.5 1237.93   455.5 1236.86
   465.5 1237.86     524  1247.7   533.8 1250.58   543.6 1255.84   553.4  1259.4
     622 1277.51   631.7    1282   690.5 1295.47   700.3 1298.52   710.1 1304.01
   778.6 1322.44   788.4 1325.88   798.2 1331.47   817.8 1337.18   856.9 1351.88
#Mann= 3 , 0 , 0
       0     .06       0   445.5    .045       0   465.5     .06       0
Bank Sta=445.5,465.5
XS Rating Curve= 0 ,0
Exp/Cntr=0.3,0.1

Type RM Length L Ch R = 1 ,6468.7  ,228.8,205.2,185.7
XS GIS Cut Line= 3
     1830270.202      321240.154     1829891.627      321334.799
     1829416.048       321541.91
#Sta/Elev= 30
       0 1370.99      40 1358.75      60 1347.46   110.1  1324.6   120.1  1319.1
   140.1 1301.81   150.1 1297.51   200.1 1283.52   210.1 1278.46   260.2 1264.23
   300.2    1254   360.2 1242.19   380.2 1233.77   390.2 1231.66   400.2 1231.67
   430.1 1233.24     460 1229.13     470 1228.88   529.9 1232.65   589.7  1238.7
   609.7 1242.62   639.6 1250.83   689.5 1266.45   709.4 1274.94   739.4 1285.51
   769.3 1291.99   789.2 1301.74   849.1 1325.94     869 1336.08     909 1352.01
#Mann= 3 , 0 , 0
       0      .1       0   380.2    .045       0   400.2      .1       0
Bank Sta=380.2,400.2
XS Rating Curve= 0 ,0
Exp/Cntr=0.3,0.1

Type RM Length L Ch R = 1 ,6263.5  ,194.3,199.9,205.6
XS GIS Cut Line= 5
     1829823.772      321059.783     1829678.136      321411.407
     1829432.787      321483.568     1829430.163      321487.504
     1829414.418       321491.44
#Sta/Elev= 30
       0 1267.04    19.5 1259.91      39 1251.84    48.8  1250.9    68.3 1243.67
    87.8  1239.7   117.1 1228.92   123.1 1227.54   126.9 1226.67   136.6 1226.53
   143.1 1226.65   234.2 1226.58   263.5 1227.58   292.8 1229.94   361.1 1237.08
   370.8 1238.57   380.6 1241.05   410.1 1246.75   439.6 1253.84   459.3 1260.66
   508.5 1274.49   528.1 1281.44     538 1286.61   547.8 1290.54     597 1307.71
   606.8 1310.46   616.7 1312.13   636.3  1319.5   641.1 1322.12   657.3 1328.01
#Mann= 3 , 0 , 0
       0      .1       0   123.1    .045       0   143.1      .1       0
Bank Sta=123.1,143.1
XS Rating Curve= 0 ,0
Exp/Cntr=0.3,0.1

Type RM Length L Ch R = 1 ,6063.6  ,376.7,406.5,436.3
XS GIS Cut Line= 3
     1830009.424      320942.848     1829637.464      321061.915
     1829353.945      321460.285
#Sta/Elev= 30
       0 1343.07   107.4  1316.2     166 1296.28   195.3 1284.47     205 1279.29
   234.3 1275.86   263.6 1269.62   283.2 1264.08   351.5 1251.66   361.3 1247.33
   420.5 1231.76   430.5 1230.26   460.4 1218.85   470.4 1216.09   481.2  1215.6
   490.3 1215.47   501.2 1217.31   510.3 1219.17   580.2  1226.6   610.1 1234.52
   679.9    1249   699.9  1254.2   709.9 1257.89   729.8 1269.41   769.8 1287.88
   789.7 1293.41   809.7  1302.1   829.6 1312.49   849.6 1325.52   879.5 1340.38
#Mann= 3 , 0 , 0
       0      .1       0   481.2    .045       0   501.2      .1       0
Bank Sta=481.2,501.2
XS Rating Curve= 0 ,0
Exp/Cntr=0.3,0.1

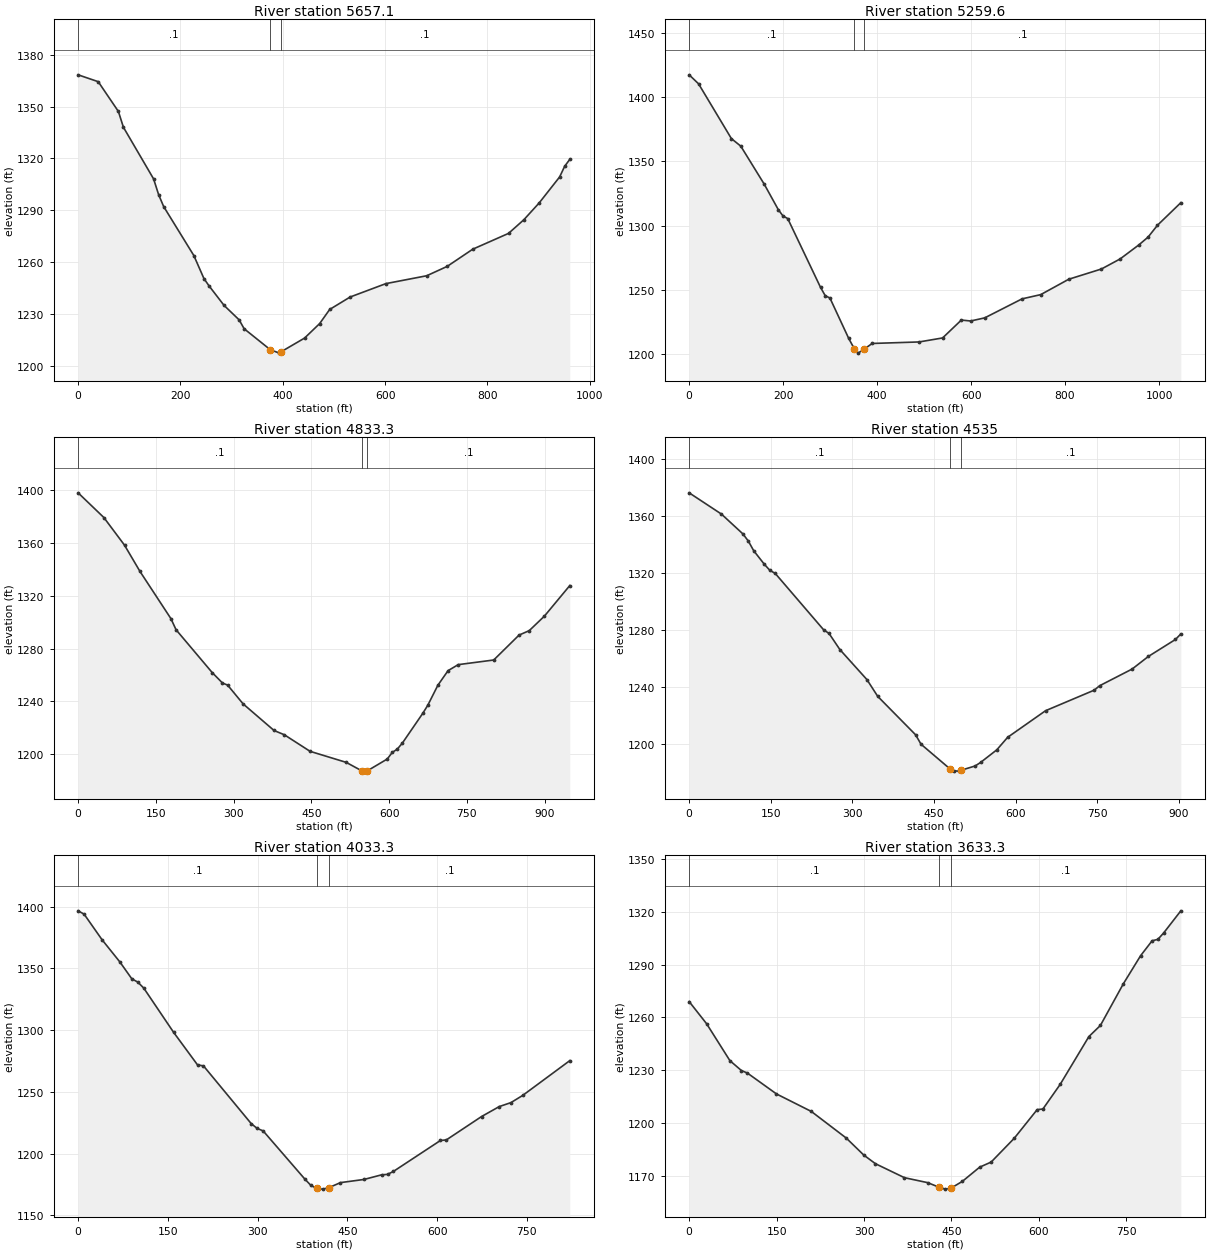
Type RM Length L Ch R = 1 ,5657.1  ,441.2,397.6,353.9
XS GIS Cut Line= 3
     1829971.047       320874.95     1829491.828       320764.74
     1829113.397      321042.281
#Sta/Elev= 30
       0 1368.48    39.3  1364.5    78.7 1347.26    88.5  1338.1   147.5 1308.16
   157.4 1298.98   167.2 1292.12   226.2 1263.72   245.9  1250.4   255.7 1246.23
   285.2 1234.86   314.7 1226.46   324.5 1221.31   375.6 1209.16   393.4 1207.18
   395.6 1207.77   442.6  1215.9   472.1 1224.31   491.7  1232.5   531.7 1239.71
   601.6 1247.47   681.4 1252.03   721.4 1257.46   771.3 1267.42   841.2 1276.57
   871.2 1284.49   901.1 1294.22   941.1 1309.29     951 1315.49     961 1319.49
#Mann= 3 , 0 , 0
       0      .1       0   375.6    .045       0   395.6      .1       0
Bank Sta=375.6,395.6
XS Rating Curve= 0 ,0
Exp/Cntr=0.3,0.1

Type RM Length L Ch R = 1 ,5259.6  ,412.3,425.5,440.8
XS GIS Cut Line= 3
     1829507.716      320129.233     1829457.715       320696.35
     1829068.282      320971.968
#Sta/Elev= 30
       0 1417.34      20 1410.36    89.9  1367.7   109.9 1361.82   159.8 1332.22
   189.8 1312.35   199.8 1307.45   209.8 1305.46   279.7 1251.83   289.6 1245.43
   299.6 1243.62   339.6 1212.14   351.6 1204.03   359.6 1200.72   371.6 1203.61
   389.5 1208.24   489.4 1209.42   539.4 1212.54   579.3 1226.46   599.1 1225.73
     629 1228.16   708.5 1242.96   748.2 1246.26   807.9 1258.24   877.4  1266.2
   917.2 1274.03     957 1284.94   976.8 1291.07   996.7 1300.26  1046.4 1317.82
#Mann= 3 , 0 , 0
       0      .1       0   351.6    .045       0   371.6      .1       0
Bank Sta=351.6,371.6
XS Rating Curve= 0 ,0
Exp/Cntr=0.3,0.1

Type RM Length L Ch R = 1 ,4833.3  ,279.5,298.3,315.2
XS GIS Cut Line= 3
     1829421.174      320087.296     1829100.506      320554.888
     1828860.337       320851.57
#Sta/Elev= 30
       0 1397.86    49.7 1379.15    89.5 1358.27   119.4 1338.36     179  1302.7
     189 1294.25   258.6 1261.91   278.5 1253.98   288.5 1252.37   318.3 1238.19
     378 1218.05   397.9 1214.81   447.6 1202.27   517.2 1193.94   547.1 1187.58
     557  1187.3   596.4 1196.44   606.1 1201.43   615.9 1203.98   625.7 1208.55
   664.9 1230.96   674.6 1237.08   694.2 1252.32   713.8 1263.32   733.4 1267.87
   801.9 1271.38   850.8 1290.24   870.4 1293.58   899.8 1304.61   948.7 1327.72
#Mann= 3 , 0 , 0
       0      .1       0   547.1    .045       0     557      .1       0
Bank Sta=547.1,557
XS Rating Curve= 0 ,0
Exp/Cntr=0.3,0.1

Type RM Length L Ch R = 1 ,4535    ,526.7,501.7,479.5
XS GIS Cut Line= 3
     1829373.433      319996.883     1829248.447       320221.56
     1828617.643      320364.642
#Sta/Elev= 30
       0 1376.52    59.3 1361.58    98.9  1347.6   108.8 1342.58   118.7 1335.78
   138.4 1326.19   148.3 1322.02   158.2 1319.86   247.2 1280.18   257.1 1277.65
     277 1266.32   326.8 1245.16   346.7 1233.34   416.3 1206.33   426.3 1199.69
   479.2 1182.46     486 1180.96   495.9 1180.77   499.2 1181.31   525.8  1184.4
   535.7 1186.86   565.6 1195.75   585.5 1204.55   655.2 1223.26   744.7 1237.73
   754.7 1240.85   814.4 1252.58   844.2 1261.43     894 1273.37   903.9 1277.26
#Mann= 3 , 0 , 0
       0      .1       0   479.2    .045       0   499.2      .1       0
Bank Sta=479.2,499.2
XS Rating Curve= 0 ,0
Exp/Cntr=0.3,0.1

Type RM Length L Ch R = 1 ,4033.3  ,398.4,399.9,395.1
XS GIS Cut Line= 3
     1828868.783      319538.211     1828724.583      319920.892
     1828536.615      320288.221
#Sta/Elev= 30
       0 1396.74      10 1394.05    39.9 1373.36    69.8 1355.28    89.8 1341.57
    99.7 1338.99   109.7 1334.09   159.6 1298.22   199.5 1271.88   209.5 1271.04
   289.3 1224.23   299.2 1220.36   309.2 1218.35     379 1179.22     389 1174.17
   398.9 1171.68     409 1171.16   418.9 1172.34   438.4 1176.44   477.7    1179
   507.2 1182.76     517 1183.12   526.8  1185.5   605.4 1210.58   615.3 1211.05
   674.2 1230.02   703.7 1238.07   723.3  1241.3     743 1247.15   821.6 1275.32
#Mann= 3 , 0 , 0
       0      .1       0   398.9    .045       0   418.9      .1       0
Bank Sta=398.9,418.9
XS Rating Curve= 0 ,0
Exp/Cntr=0.3,0.1

Type RM Length L Ch R = 1 ,3633.3  ,397.1,414.4,435.1
XS GIS Cut Line= 3
     1828522.609      319434.126     1828340.919      319834.041
        1828228.      320222.199
#Sta/Elev= 30
       0 1269.05      30  1256.4    69.9 1235.41    89.8 1229.74    99.8 1228.37
   149.8 1216.46   209.6 1206.49   269.5 1191.34   299.5 1181.68   319.5 1176.75
   369.4 1168.77   409.3 1165.94   429.3 1163.26   439.2 1162.26   449.3 1162.83
   468.8  1166.7   498.4 1174.77   518.1 1177.67   557.6 1191.17     597 1207.51
   606.9 1207.88   636.4 1221.84   685.8 1249.13   705.5 1255.44   744.9 1279.18
   774.5 1295.16   794.2 1303.65   804.1 1304.46   813.9 1308.05   843.5 1320.71
#Mann= 3 , 0 , 0
       0      .1       0   429.3    .045       0   449.3      .1       0
Bank Sta=429.3,449.3
XS Rating Curve= 0 ,0
Exp/Cntr=0.3,0.1

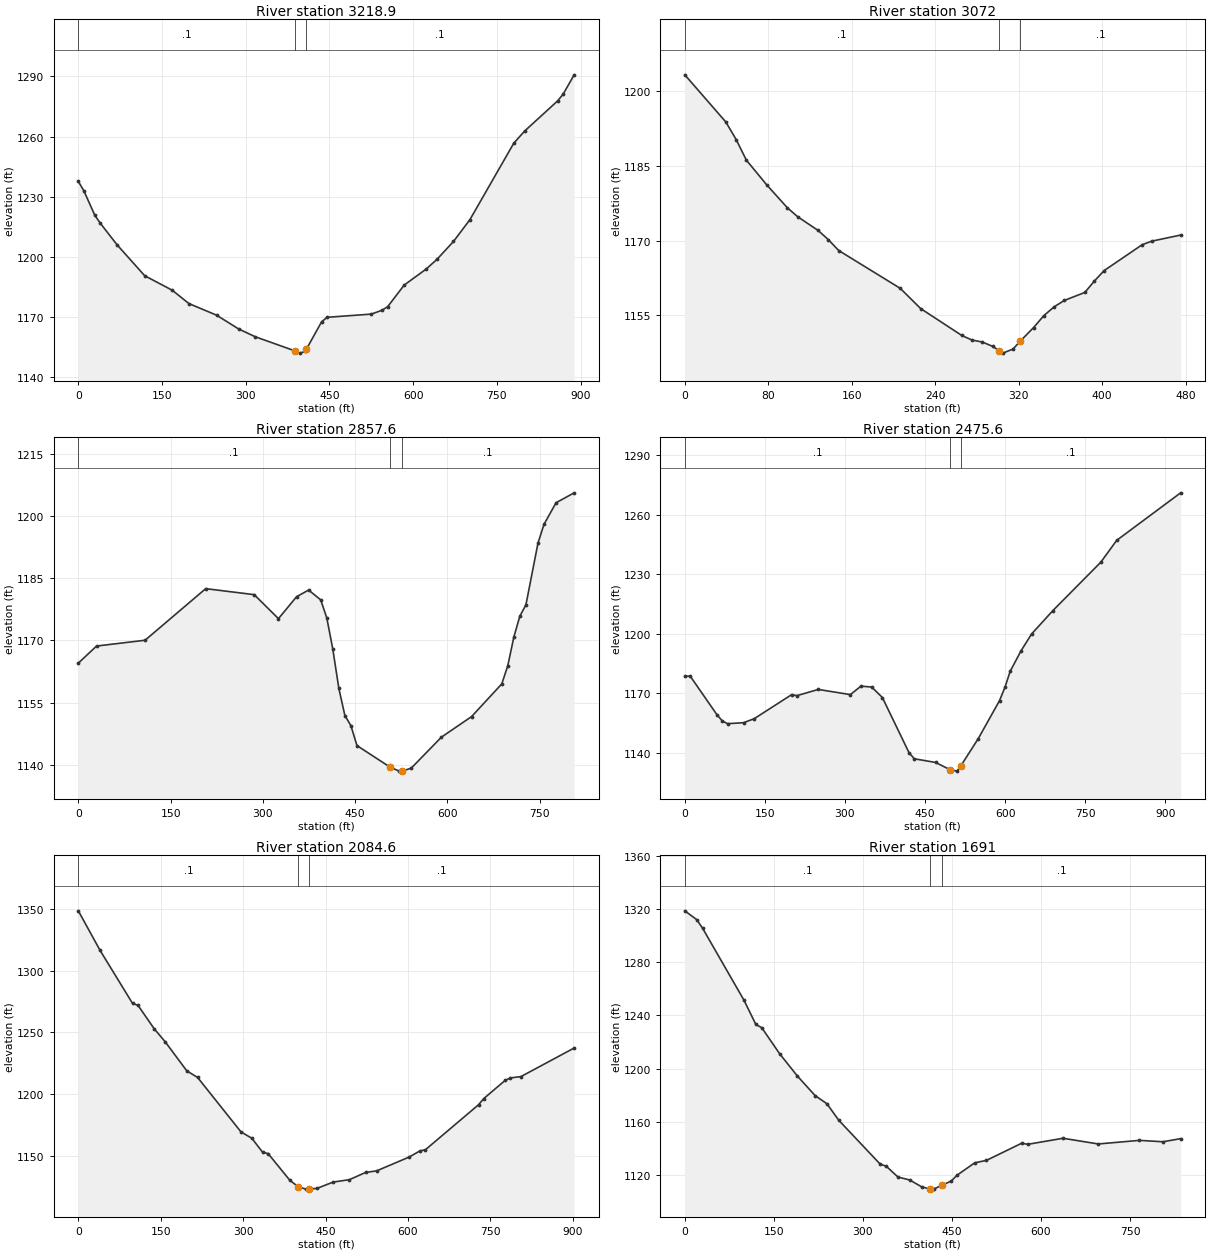
Type RM Length L Ch R = 1 ,3218.9  ,146.3,147,147.7
XS GIS Cut Line= 3
     1828436.143       319360.64     1827984.634      319587.357
     1827812.738       319929.74
#Sta/Elev= 30
       0 1237.71     9.9 1233.03    29.7 1220.74    39.6 1216.79    69.4 1206.11
   118.9 1190.71   168.4 1183.46   198.1 1176.84   247.7 1171.05   287.3 1164.17
     317  1160.3   388.5 1153.21   396.3 1152.14   406.2 1152.97   408.5 1154.03
   435.9 1167.75   445.8    1170   524.9 1171.58   544.5 1173.55   554.4 1175.33
   583.8 1186.04   623.1    1194   642.8 1198.92   672.2 1207.79   701.7 1218.69
   780.3 1256.78   799.9 1262.87   858.9 1277.86   868.7 1281.21   888.4 1290.82
#Mann= 3 , 0 , 0
       0      .1       0   388.5    .045       0   408.5      .1       0
Bank Sta=388.5,408.5
XS Rating Curve= 0 ,0
Exp/Cntr=0.3,0.1

Type RM Length L Ch R = 1 ,3072    ,246.4,215.4,184.3
XS GIS Cut Line= 3
      1828303.88      319272.997     1827956.466      319435.292
     1827965.341      319526.584
#Sta/Elev= 30
       0 1203.23    39.3 1193.78    49.2 1190.26      59 1186.12    78.7 1181.12
    98.3 1176.57   108.2 1174.77   127.8 1172.02   137.6 1170.17   147.5    1168
   206.5 1160.41   226.1 1156.35   265.5 1150.96   275.3 1150.04   285.1 1149.65
     295 1148.78   301.4 1147.89   304.8 1147.42   314.6 1148.24   321.4 1149.81
   334.3 1152.55   344.1 1154.94     354 1156.71   363.8 1157.99   383.4 1159.59
   392.6 1161.89   401.8 1163.96   438.5 1169.18   447.7 1169.88   475.2  1171.1
#Mann= 3 , 0 , 0
       0      .1       0   301.4    .045       0   321.4      .1       0
Bank Sta=301.4,321.4
XS Rating Curve= 0 ,0
Exp/Cntr=0.3,0.1

Type RM Length L Ch R = 1 ,2857.6  ,346,380.9,416.7
XS GIS Cut Line= 3
     1828032.031      318958.756     1827815.382      319201.621
      1827898.04      319675.263
#Sta/Elev= 30
       0 1164.53    29.6 1168.65   108.5 1170.05   207.1  1182.5     286 1181.05
   325.4 1175.26   354.9 1180.56   374.5 1182.16   394.1 1179.79     404 1175.44
   413.8 1167.88   423.6 1158.41   433.4 1151.89   443.2 1149.45     453 1144.64
   506.6 1139.46   521.7 1138.47   526.6 1138.48   541.3 1139.19   590.4 1146.67
   639.4 1151.63   688.5 1159.51   698.3 1163.91   708.1  1170.8   717.9 1175.86
   727.8 1178.61   747.4  1193.5   757.2 1198.03   776.8 1203.23   806.2 1205.62
#Mann= 3 , 0 , 0
       0      .1       0   506.6    .045       0   526.6      .1       0
Bank Sta=506.6,526.6
XS Rating Curve= 0 ,0
Exp/Cntr=0.3,0.1

Type RM Length L Ch R = 1 ,2475.6  ,411.2,390.9,369.7
XS GIS Cut Line= 3
      1827899.68      318924.127     1827780.286      319274.438
     1827242.331      319425.365
#Sta/Elev= 30
       0 1178.44      10 1178.65      60 1159.23      70  1156.1      80 1154.63
     110 1155.12     130 1157.14     200 1169.25   210.1 1168.76   250.1 1171.89
   310.1 1169.28   330.1 1173.56   350.1 1173.09   370.1 1167.82     420 1140.03
     430 1136.93   469.9 1135.08   496.5 1131.48   509.8 1130.71   516.5 1133.13
   549.7 1147.08   589.6 1166.28   599.6 1172.88   609.6 1181.09   629.5  1191.2
   649.5 1199.81   689.4 1211.62   779.2 1236.01   809.1 1247.06   928.8 1271.01
#Mann= 3 , 0 , 0
       0      .1       0   496.5    .045       0   516.5      .1       0
Bank Sta=496.5,516.5
XS Rating Curve= 0 ,0
Exp/Cntr=0.3,0.1

Type RM Length L Ch R = 1 ,2084.6  ,391.7,393.4,397
XS GIS Cut Line= 3
     1827681.507      318624.315     1827403.733      319191.781
     1827176.063      319338.558
#Sta/Elev= 30
       0 1348.64    39.5 1316.58    98.7 1273.49   108.6 1271.93   138.2 1252.86
     158 1242.42   197.4 1218.78   217.2 1213.35   296.2 1169.16   315.9 1164.03
   335.6 1152.61   345.5 1151.62     385 1129.94   400.4  1124.6   414.6 1122.74
   420.4 1122.91   434.4 1123.32     464 1128.47   493.6 1130.43   523.2 1136.31
     543 1137.54   602.2 1148.76   621.9 1153.77   631.8 1154.67   728.6 1191.23
   738.2 1196.27   776.9 1210.94   786.6    1213   805.9 1214.11   902.7 1237.29
#Mann= 3 , 0 , 0
       0      .1       0   400.4    .045       0   420.4      .1       0
Bank Sta=400.4,420.4
XS Rating Curve= 0 ,0
Exp/Cntr=0.3,0.1

Type RM Length L Ch R = 1 ,1691    ,397.8,399.8,398.1
XS GIS Cut Line= 3
     1827341.858       318500.12      1827127.17      318871.492
     1826889.873      319201.269
#Sta/Elev= 30
       0 1318.85      20 1312.25    29.9 1305.79    99.8 1251.43   119.7 1233.24
   129.7 1230.76   159.6 1211.29   189.5 1194.46   219.5 1179.67   239.4 1173.53
   259.4 1161.06   329.2 1127.98   339.2 1126.52   359.1  1118.3   379.1 1116.06
     399 1110.91   413.1 1109.26     419  1109.2   433.1 1112.08   448.8 1115.29
   458.7 1119.73   488.4 1129.01   508.2 1130.88   567.7 1143.82   577.6 1142.95
   637.1 1147.51   696.5 1143.23   765.9 1145.93   805.5 1144.88   835.2 1147.22
#Mann= 3 , 0 , 0
       0      .1       0   413.1    .045       0   433.1      .1       0
Bank Sta=413.1,433.1
XS Rating Curve= 0 ,0
Exp/Cntr=0.3,0.1

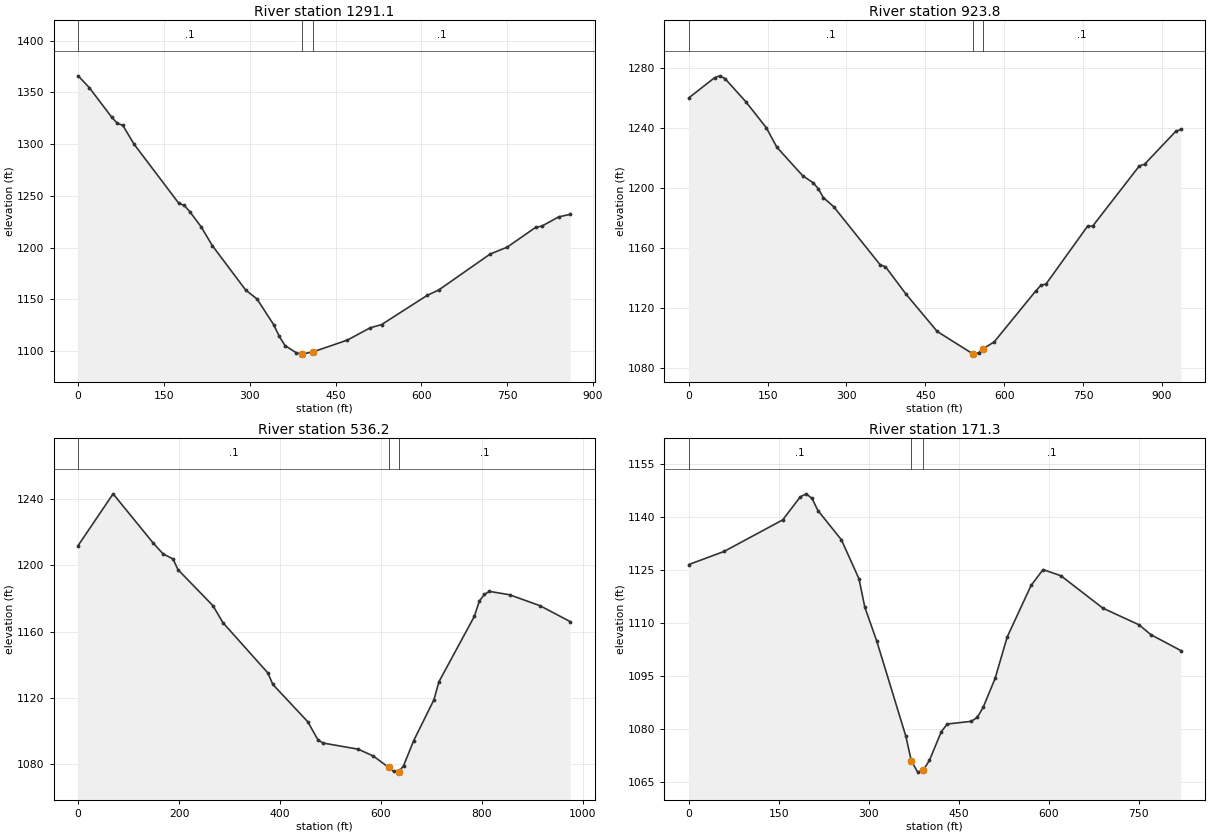
Type RM Length L Ch R = 1 ,1291.1  ,380,367.3,356.7
XS GIS Cut Line= 3
     1827097.536      318249.641      1826868.44      318578.342
     1826635.324      318974.415
#Sta/Elev= 30
       0 1366.12    19.5 1354.71    58.6 1326.19    68.4  1320.3    78.2 1318.15
    97.7  1300.1   175.9 1242.95   185.7 1240.77   195.4 1234.65     215 1220.19
   234.5 1202.06   293.2 1158.81   312.7 1150.42     342 1125.36   351.8 1114.11
   361.6 1105.36   381.1 1098.46   390.7 1097.04   410.7 1099.23   470.6 1110.59
   510.6 1122.48   530.5 1125.59   610.5 1153.94   630.4 1159.04   720.4  1193.8
   750.3 1200.52   800.3 1219.77   810.3 1220.69   840.3 1229.77   860.2 1232.17
#Mann= 3 , 0 , 0
       0      .1       0   390.7    .045       0   410.7      .1       0
Bank Sta=390.7,410.7
XS Rating Curve= 0 ,0
Exp/Cntr=0.3,0.1

Type RM Length L Ch R = 1 ,923.8   ,348.6,387.5,426.4
XS GIS Cut Line= 3
     1826839.522      318130.822     1826526.641      318430.475
     1826473.042      318930.459
#Sta/Elev= 30
       0 1260.23    49.2 1273.71    59.1 1274.92    68.9 1273.07   108.3 1257.71
   147.7 1240.19   167.4 1227.36   216.6 1208.32   236.3 1203.68   246.2 1199.74
     256 1193.71   275.7 1187.62   364.3 1148.79   374.2 1147.58   413.5 1129.23
   472.7 1104.41   539.8 1089.62   541.7 1089.31   551.5 1090.25   559.8 1092.87
   581.1  1097.5     660  1131.4   669.9 1135.21   679.7 1136.09   758.6  1174.6
   768.5 1174.75   857.2 1214.84   867.1 1215.93   926.2 1237.81   936.1 1239.17
#Mann= 3 , 0 , 0
       0      .1       0   539.8    .045       0   559.8      .1       0
Bank Sta=539.8,559.8
XS Rating Curve= 0 ,0
Exp/Cntr=0.3,0.1

Type RM Length L Ch R = 1 ,536.2   ,369.5,364.8,360.1
XS GIS Cut Line= 3
     1826788.535      318057.591     1826419.383      318340.437
     1825910.822      318301.301
#Sta/Elev= 30
       0 1211.95    69.3 1243.14   148.4 1213.58   168.2 1206.93     188 1203.84
   197.9 1197.37   267.2 1175.63     287  1165.4     376 1135.05   385.9 1128.12
   455.2 1105.58     475 1094.81   485.1 1092.76   555.1 1089.05   585.1 1084.91
   615.3 1078.06   625.1 1075.61   635.1  1075.2   635.3 1075.28   645.1 1079.18
   665.1 1094.24   705.1 1118.83   715.1 1129.76   785.1 1169.12   795.1 1178.39
   805.1 1182.43   815.1 1184.28   855.1 1182.22   915.1 1175.66   975.1 1166.06
#Mann= 3 , 0 , 0
       0      .1       0   615.3    .045       0   635.3      .1       0
Bank Sta=615.3,635.3
XS Rating Curve= 0 ,0
Exp/Cntr=0.3,0.1

Type RM Length L Ch R = 1 ,171.3   ,169.5,171.3,173.1
XS GIS Cut Line= 3
     1826763.323      317957.342     1826355.452      318006.436
     1825946.639      318025.722
#Sta/Elev= 30
       0 1126.57    58.7 1130.27   156.5 1139.21   185.8 1145.73   195.6 1146.59
   205.4 1145.29   215.2 1141.86   254.3 1133.59   283.7 1122.51   293.4 1114.46
     313 1105.04   361.9 1077.89   370.9 1070.96   381.5  1067.8   390.9 1068.36
     401 1071.12   420.8 1079.22   430.8 1081.42   470.7 1082.18   480.7 1083.27
   490.7 1086.15   510.6 1094.36   530.6 1106.02   570.5 1120.65   590.5 1125.15
   620.4 1123.38   690.3 1114.21   750.2 1109.53   770.2 1106.72   820.1 1102.22
#Mann= 3 , 0 , 0
       0      .1       0   370.9    .045       0   390.9      .1       0
Bank Sta=370.9,390.9
XS Rating Curve= 0 ,0
Exp/Cntr=0.3,0.1

Chan Stop Cuts=-1
Use User Specified Reach Order=0
Composite Channel Slope=5